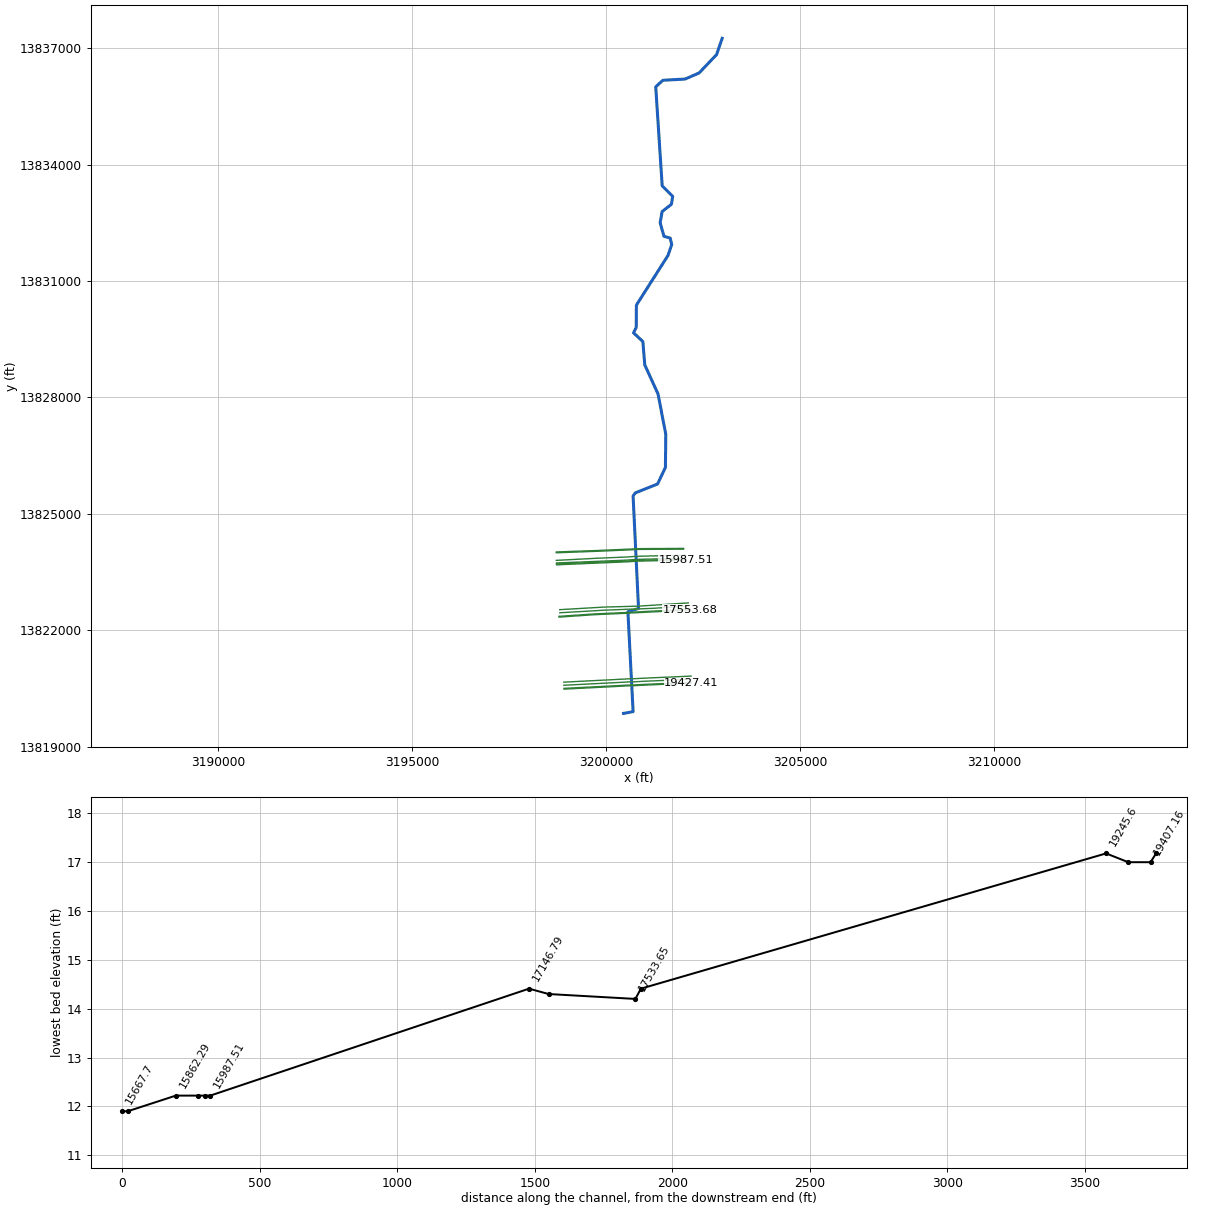
--- G104-00-00.prj (project) ---

Proj Title=G104-00-00
Current Plan=p01
Default Exp/Contr=.3,.1
English Units
Geom File=g01
Flow File=f01
Flow File=f02
Plan File=p01
Plan File=p02
Y Axis Title=Elevation
X Axis Title(PF)=Main Channel Distance
X Axis Title(XS)=Station
BEGIN DESCRIPTION:
HCFCD MODEL SUMMARY METADATA
The purpose of this summary is to document the high points of hydrologic and hydraulic models filed within the HCFCD Model and Map Management (M3) system.  The document includes references to the project that prompted the creation or update of the model.
DESCRIPTION OF PROJECT:
The following model was the hydraulic model which represented the effective condition of Harris County's watersheds.
PURPOSE OF PROJECT:
Development of effective models to support the National Flood Insurance Program.
HCFCD Watershed Unit ID: G
M3 Study Identifier: 2007_Effective_G
Engineer: HCFCD
Project Name: EffectiveFEMA Study for watershed San Jancinto River (G)
Study Completion Date: 6/18/2007
FEMA Case Number: [No Data]
FEMA Approval Date: [No Date in Database]
Vertical Datum: NAVD 1988
Datum Note: 2001 ADJ
HYDRAULICS
HCFCD Unit No.:  G104-00-00
Hydraulic Program Name: HEC-RAS
Hydraulic Program Version: 3.0.1
Steady Hydraulic Model: Yes
Unsteady Hydraulic Model: No
Update 1: The effective FEMA hydraulic model for unit number G104-00-00 has been updated by FEMA LOMR 16-06-0467P with an effective date of 11/18/2016.
END DESCRIPTION:
DSS File=dss
DSS Export Rating Curves= 0
DSS Export Rating Curve Sorted= 0
DSS Export Volume Flow Curves= 0
DXF OffsetX= 0
DXF OffsetY= 0
DXF ScaleX= 1
DXF ScaleY= 10

--- G104-00-00.p01 (plan) ---

Plan Title=FEMA Effective Multi-Profile 2016
Version=Version 3.0.1  May 2012
Short Identifier=Eff+LOMR MP
Geom File=g01
Flow File=f01
Subcritical Flow
K Sum by GR= 0
Std Step Tol= 0.01
Critical Tol= 0.01
Num of Std Step Trials= 20
Max Error Tol= 0.3
Flow Tol Ratio= 0.001
Split Flow NTrial= 30
Split Flow Tol= 0.02
Split Flow Ratio= 0.02
Log Output Level= 0
Friction Slope Method= 0
Unsteady Friction Slope Method= 2
Secant Critical Depth
Global Vel Dist= 0 , 0 , 0
Global Log Level= 0
CheckData=True
Encroach Param=-1 ,0,0, 0
BEGIN DESCRIPTION:
FEMA Effective Multi-Profile June 2007 + LOMR 16-06-0467P
END DESCRIPTION:
Computation Interval=1HOUR
Output Interval=1HOUR
Run HTab= 0
Run UNet= 0
Run PostProcess= 0
UNET Theta= 1
UNET ZTol= 0.02
UNET ZSATol= 0.1
UNET MxIter= 20
UNET MaxInSteps= 20
UNET DtIC= 0
UNET DtMin= 0
UNET MaxCRTS= 20
UNET WFStab= 2
UNET SFStab= 1
UNET WFX= 1
UNET SFX= 1
UNET Convert EG Bridges=-1
UNET Use Existing IB Tables=-1
Instantaneous Interval=1HOUR
Write IC File= 0
IC Time=0
Write Velocity= 0
Write Detailed= 0

--- G104-00-00.p02 (plan) ---

Plan Title=FEMA Effective Floodway 2016
Version=Version 3.0.1  May 2012
Short Identifier=Eff+LOMR FW
Geom File=g01
Flow File=f02
Subcritical Flow
K Sum by GR= 0
Std Step Tol= 0.01
Critical Tol= 0.01
Num of Std Step Trials= 20
Max Error Tol= 0.3
Flow Tol Ratio= 0.001
Split Flow NTrial= 30
Split Flow Tol= 0.02
Split Flow Ratio= 0.02
Log Output Level= 0
Friction Slope Method= 0
Unsteady Friction Slope Method= 2
Secant Critical Depth
Global Vel Dist= 0 , 0 , 0
Global Log Level= 0
CheckData=True
Encroach Param=-1 ,0,0, 2
Encroach River=G104-00-00
Encroach Reach=G104-00-00_0015
Encroach Node=19427.41
       1 4964.75 5030.98
Encroach Node=19407.16
       1 4964.75 5030.98
Encroach Node=19367
       1 4964.75 5035.98
Encroach Node=19326.06
       1 4969.75 5035.98
Encroach Node=19245.6
       1 4974.75 5040.98
Encroach Node=17553.68
       1    4968 5043.21
Encroach Node=17533.65
       1 4955.41 5038.21
Encroach Node=17376
       1 4955.41  5126.7
Encroach Node=17218.29
       1  5033.8  5126.7
Encroach Node=17146.79
       1  4941.1    5045
Encroach Node=15987.51
       1 4969.87 5030.13
Encroach Node=15967.54
       1 4969.87 5030.13
Encroach Node=15954
       1 4969.87 5030.13
Encroach Node=15941.97
       1 4969.87 5030.13
Encroach Node=15862.29
       1 4969.87 5030.13
Encroach Node=15687.69
       1 4970.86    5030
Encroach Node=15667.7
       1  4971.5 5029.14
Encroach Node=15652
       1 4970.86  5036.4
Encroach Node=15637.72
       1 4970.86  5036.4
Encroach Node=15563.42
       1 4970.86  5031.8
Encroach Node=15422.84
       1 4955.33 5024.67
Encroach Node=15402.71
       1 4965.33 5034.67
Encroach Node=15365
       1 4965.33 5034.67
Encroach Node=15327.45
       1 4965.33 5034.67
Encroach Node=15247.42
       1 4965.33 5034.67
Encroach Node=14888.08
       1  4964.6  5035.4
Encroach Node=14872.95
       1  4964.6  5035.4
Encroach Node=14840
       1  4964.6  5035.4
Encroach Node=14807.6
       1  4964.6  5035.4
Encroach Node=14727.31
       1  4964.6  5035.4
Encroach Node=14616.54
       1 4957.83    5037
Encroach Node=14596.51
       1 4957.83    5040
Encroach Node=14581
       1 4957.83    5040
Encroach Node=14565.32
       1 4957.83    5039
Encroach Node=14487.08
       1 4957.83    5051
Encroach Node=13434.89
       1 4972.27 5027.73
Encroach Node=13016.05
       1    4800    5200
Encroach Node=13001.24
       1    4900    5100
Encroach Node=12940
       1 4932.37    5046
Encroach Node=11918
       1 4951.84 5064.02
Encroach Node=11154.16
       1 4951.84 5064.02
Encroach Node=10950.47
       1 4932.14 5117.38
Encroach Node=9080.683
       1 4805.92 5040.84
Encroach Node=8980.683
       1 4903.07 5054.62
Encroach Node=8913
       1 4903.07 5054.62
Encroach Node=8846.768
       1 4874.94 5043.16
Encroach Node=8644.219
       1  4910.4  5089.6
Encroach Node=7359.369
       1 4568.53 5470.37
Encroach Node=6592.418
       1  4633.3 5300.41
Encroach Node=6486.955
       1    4693 5348.98
Encroach Node=6468
       1    4693 5432.07
Encroach Node=6449.087
       1  4767.5 5432.07
Encroach Node=6288.545
       1 4847.42 5422.86
Encroach Node=4116.345
       1 4901.56 5098.44
Encroach Node=2106.104
       1 4702.36 5139.48
Encroach Node=2002.826
       1 4817.86 5081.58
Encroach Node=1975
       1 4817.86    5108
Encroach Node=1948.456
       1    4905    5108
Encroach Node=1851.577
       1  4806.2 5208.22
Encroach Node=1481.128
       1 4765.87 5200.69
BEGIN DESCRIPTION:
FEMA Effective Floodway June 2007 + LOMR 16-06-0467P
END DESCRIPTION:
Computation Interval=1HOUR
Output Interval=1HOUR
Run HTab= 0
Run UNet= 0
Run PostProcess= 0
UNET Theta= 1
UNET ZTol= 0.02
UNET ZSATol= 0.1
UNET MxIter= 20
UNET MaxInSteps= 20
UNET DtIC= 0
UNET DtMin= 0
UNET MaxCRTS= 20
UNET WFStab= 2
UNET SFStab= 1
UNET WFX= 1
UNET SFX= 1
UNET Convert EG Bridges=-1
UNET Use Existing IB Tables=-1
Instantaneous Interval=1HOUR
Write IC File= 0
IC Time=0
Write Velocity= 0
Write Detailed= 0

--- G104-00-00.f01 (steady flow) ---

Flow Title=FEMA Effective Multi-Profile 2016
Program Version=3.0.1
Number of Profiles= 4
Profile Names=10PCT_10yr, 2PCT_50yr, 1PCT_100yr, 0.2PCT_500yr
River Rch & RM=G104-00-00,G104-00-00_0015 ,19427.41
     181     249     285     378
River Rch & RM=G104-00-00,G104-00-00_0015 ,19326.06
     187     257     295     390
River Rch & RM=G104-00-00,G104-00-00_0015 ,19245.6
     374     513     587     777
River Rch & RM=G104-00-00,G104-00-00_0015 ,17553.68
     377     517     591     784
River Rch & RM=G104-00-00,G104-00-00_0015 ,17533.65
     429     588     673     892
River Rch & RM=G104-00-00,G104-00-00_0015 ,17218.29
     436     598     683     906
River Rch & RM=G104-00-00,G104-00-00_0015 ,17146.79
     566     777     888    1177
River Rch & RM=G104-00-00,G104-00-00_0015 ,15987.51
     703     908    1017    1291
River Rch & RM=G104-00-00,G104-00-00_0015 ,15862.29
     731     945    1058    1343
River Rch & RM=G104-00-00,G104-00-00_0015 ,15687.69
     752     972    1088    1382
River Rch & RM=G104-00-00,G104-00-00_0015 ,15563.42
     776    1003    1123    1426
River Rch & RM=G104-00-00,G104-00-00_0015 ,15422.84
     793    1024    1148    1457
River Rch & RM=G104-00-00,G104-00-00_0015 ,15327.45
     799    1033    1157    1469
River Rch & RM=G104-00-00,G104-00-00_0015 ,15247.42
     831    1073    1202    1526
River Rch & RM=G104-00-00,G104-00-00_0015 ,14872.95
     864    1116    1250    1587
River Rch & RM=G104-00-00,G104-00-00_0015 ,14487.08
     962    1242    1391    1767
River Rch & RM=G104-00-00,G104-00-00_0015 ,13434.89
    1655    2218    2515    3290
River Rch & RM=G104-00-00,G104-00-00_0015 ,13016.05
    1079    1241    1299    1686
River Rch & RM=G104-00-00,G104-00-00_0015 ,13001.24
    1224    1404    1470    1897
River Rch & RM=G104-00-00,G104-00-00_0015 ,12940
    1445    1769    1902    2411
River Rch & RM=G104-00-00,G104-00-00_0015 ,11154.16
    1464    1793    1928    2441
River Rch & RM=G104-00-00,G104-00-00_0015 ,10950.47
    1657    2026    2180    2742
River Rch & RM=G104-00-00,G104-00-00_0015 ,9080.683
    1667    2039    2194    2759
River Rch & RM=G104-00-00,G104-00-00_0015 ,8980.683
    1682    2057    2213    2782
River Rch & RM=G104-00-00,G104-00-00_0015 ,8846.768
    1756    2222    2447    3143
River Rch & RM=G104-00-00,G104-00-00_0015 ,8644.219
    1975    2491    2741    3488
River Rch & RM=G104-00-00,G104-00-00_0015 ,7359.369
    2117    2665    2931    3710
River Rch & RM=G104-00-00,G104-00-00_0015 ,6592.418
    3010    4000    4487    5885
River Rch & RM=G104-00-00,G104-00-00_0015 ,4116.345
    3205    4251    4770    6255
Boundary for River Rch & Prof#=East 13 Street,G104-08-00      , 1
Up Type= 0
Dn Type= 0
Boundary for River Rch & Prof#=East 13 Street,G104-08-00      , 2
Up Type= 0
Dn Type= 0
Boundary for River Rch & Prof#=East 13 Street,G104-08-00      , 3
Up Type= 0
Dn Type= 0
Boundary for River Rch & Prof#=East 13 Street,G104-08-00      , 4
Up Type= 0
Dn Type= 0
Boundary for River Rch & Prof#=G104-00-00,G104-00-00_0015 , 1
Up Type= 0
Dn Type= 1
Dn Known WS=1.5
Boundary for River Rch & Prof#=G104-00-00,G104-00-00_0015 , 2
Up Type= 0
Dn Type= 1
Dn Known WS=1.5
Boundary for River Rch & Prof#=G104-00-00,G104-00-00_0015 , 3
Up Type= 0
Dn Type= 1
Dn Known WS=1.5
Boundary for River Rch & Prof#=G104-00-00,G104-00-00_0015 , 4
Up Type= 0
Dn Type= 1
Dn Known WS=1.5
Boundary for River Rch & Prof#=Patrick,G104-00-00 Lower, 1
Up Type= 0
Dn Type= 1
Dn Known WS=1.5
Boundary for River Rch & Prof#=Patrick,G104-00-00 Lower, 2
Up Type= 0
Dn Type= 1
Dn Known WS=1.5
Boundary for River Rch & Prof#=Patrick,G104-00-00 Lower, 3
Up Type= 0
Dn Type= 1
Dn Known WS=1.5
Boundary for River Rch & Prof#=Patrick,G104-00-00 Lower, 4
Up Type= 0
Dn Type= 1
Dn Known WS=1.5
DSS Import GetInterval= 0
DSS Import GetPeak= 0
DSS Import FillOption= 0

--- G104-00-00.f02 (steady flow) ---

Flow Title=FEMA Effective Floodway 2016
Program Version=3.0.1
Number of Profiles= 2
Profile Names=1PCT_100yr,1PCTFloodway_100yr
River Rch & RM=G104-00-00,G104-00-00_0015 ,19427.41
     285     285
River Rch & RM=G104-00-00,G104-00-00_0015 ,19326.06
     295     295
River Rch & RM=G104-00-00,G104-00-00_0015 ,19245.6
     587     587
River Rch & RM=G104-00-00,G104-00-00_0015 ,17553.68
     591     591
River Rch & RM=G104-00-00,G104-00-00_0015 ,17533.65
     673     673
River Rch & RM=G104-00-00,G104-00-00_0015 ,17218.29
     683     683
River Rch & RM=G104-00-00,G104-00-00_0015 ,17146.79
     888     888
River Rch & RM=G104-00-00,G104-00-00_0015 ,15987.51
    1017    1017
River Rch & RM=G104-00-00,G104-00-00_0015 ,15862.29
    1058    1058
River Rch & RM=G104-00-00,G104-00-00_0015 ,15687.69
    1088    1088
River Rch & RM=G104-00-00,G104-00-00_0015 ,15563.42
    1123    1123
River Rch & RM=G104-00-00,G104-00-00_0015 ,15422.84
    1148    1148
River Rch & RM=G104-00-00,G104-00-00_0015 ,15327.45
    1157    1157
River Rch & RM=G104-00-00,G104-00-00_0015 ,15247.42
    1202    1202
River Rch & RM=G104-00-00,G104-00-00_0015 ,14872.95
    1250    1250
River Rch & RM=G104-00-00,G104-00-00_0015 ,14487.08
    1391    1391
River Rch & RM=G104-00-00,G104-00-00_0015 ,13434.89
    2515    2515
River Rch & RM=G104-00-00,G104-00-00_0015 ,13016.05
    1299    1299
River Rch & RM=G104-00-00,G104-00-00_0015 ,13001.24
    1470    1470
River Rch & RM=G104-00-00,G104-00-00_0015 ,12940
    1902    1902
River Rch & RM=G104-00-00,G104-00-00_0015 ,11154.16
    1928    1928
River Rch & RM=G104-00-00,G104-00-00_0015 ,10950.47
    2180    2180
River Rch & RM=G104-00-00,G104-00-00_0015 ,9080.683
    2194    2194
River Rch & RM=G104-00-00,G104-00-00_0015 ,8980.683
    2213    2213
River Rch & RM=G104-00-00,G104-00-00_0015 ,8846.768
    2447    2447
River Rch & RM=G104-00-00,G104-00-00_0015 ,8644.219
    2741    2741
River Rch & RM=G104-00-00,G104-00-00_0015 ,7359.369
    2931    2931
River Rch & RM=G104-00-00,G104-00-00_0015 ,6592.418
    4487    4487
River Rch & RM=G104-00-00,G104-00-00_0015 ,4116.345
    4770    4770
Boundary for River Rch & Prof#=G104-00-00,G104-00-00_0015 , 1
Up Type= 0
Dn Type= 1
Dn Known WS=1.5
Boundary for River Rch & Prof#=G104-00-00,G104-00-00_0015 , 2
Up Type= 0
Dn Type= 1
Dn Known WS=2.5
DSS Import GetInterval= 0
DSS Import GetPeak= 0
DSS Import FillOption= 0

--- G104-00-00.g01 (geometry) ---

Geom Title=G104-00-00
Program Version=3.0.1

River Reach=G104-00-00      ,G104-00-00_0015
Reach XY= 30
        3200450.       13819854.       3200696.7    13819897.901
     3200562.409    13822471.364     3200836.473    13822559.065
        3200696.       13825458.        3200754.       13825538.
      3201326.25       13825765.      3201529.25       13826194.
      3201539.75       13827040.       3201339.5       13828085.
        3200997.       13828837.        3200948.       13829438.
        3200707.       13829664.      3200776.25       13829802.
       3200781.5       13830378.      3201594.75       13831655.
       3201691.5       13831936.        3201654.       13832104.
       3201491.5       13832151.      3201393.25       13832501.
      3201445.25       13832790.      3201682.75       13832974.
      3201717.25       13833180.      3201445.75       13833452.
      3201279.75       13836003.       3201463.5       13836173.
      3202035.25       13836204.        3202396.       13836360.
       3202847.5       13836834.      3202992.25       13837254.

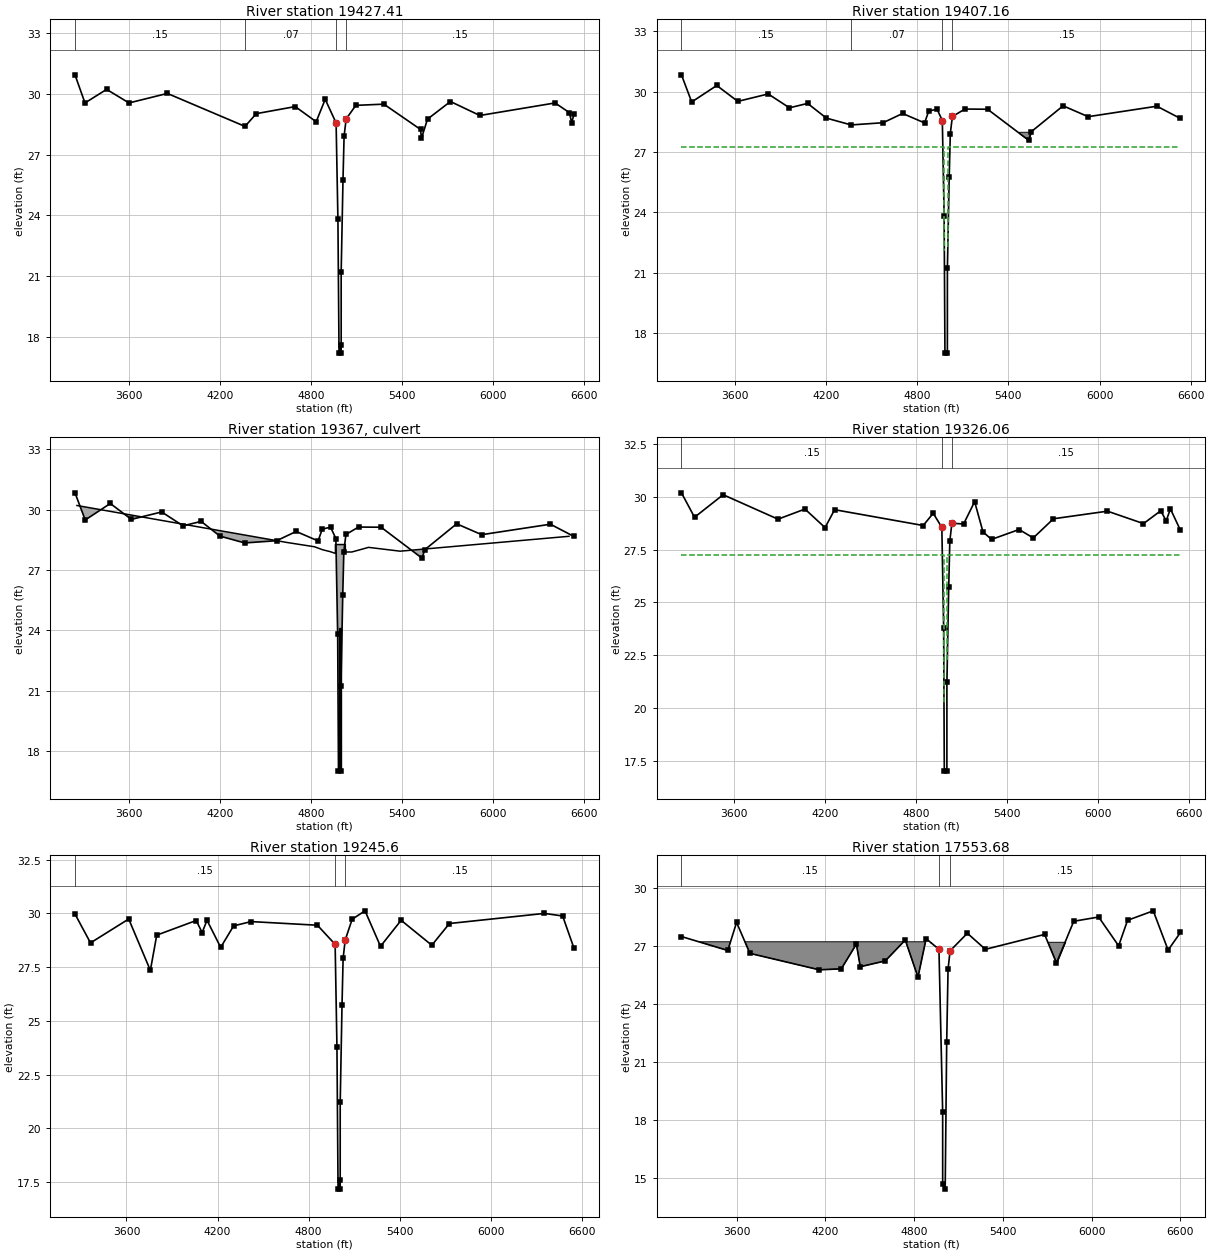
Type RM Length L Ch R = 1 ,19427.41,20.03,20.24,20.03
BEGIN DESCRIPTION:
East X Street
END DESCRIPTION:
XS GIS Cut Line= 6
     3198917.895    13820478.904     3200336.671    13820551.168
     3200636.576    13820566.923     3200698.548    13820566.248
     3200974.894     13820581.09     3202199.833    13820635.052
#Sta/Elev= 30
  3245.4   30.94  3311.1   29.55 3453.58   30.22  3601.2   29.55 3853.62   30.02
  4364.8   28.39 4439.16   29.02  4695.6   29.37 4833.44   28.62    4893   29.73
 4964.75   28.56 4976.67   23.79 4983.99    17.2 4997.89   17.59 4998.08   17.18
 4998.15   21.21 5010.06   25.74  5017.3   27.91 5030.98   28.76 5094.66   29.43
  5279.2   29.49 5520.54   28.24  5526.6    27.8 5566.58   28.75  5717.6   29.62
  5911.3   28.93 6406.86   29.55 6500.62   29.07 6516.12   28.58 6531.18   28.99
#Mann= 4 ,-1 , 0
  3245.4     .15       0  4364.8     .07       0 4964.75    .015       0
 5030.98     .15       0
#Block Obstruct= 1 ,-1
 5519.74 5537.78      28
Bank Sta=4964.75,5030.98
XS Rating Curve= 0 ,0
Exp/Cntr=0.5,0.3

Type RM Length L Ch R = 1 ,19407.16,80.1,81.1,80.11
BEGIN DESCRIPTION:
East X Street
END DESCRIPTION:
XS GIS Cut Line= 6
     3198916.877    13820498.879     3200335.638    13820571.141
      3200636.16    13820586.929      3200698.12    13820586.254
     3200973.918    13820601.066     3202198.953    13820655.033
#Sta/Elev= 30
 3246.96   30.83 3314.32   29.48 3479.48    30.3 3618.18   29.51 3817.98   29.88
  3958.2   29.19 4077.66   29.41 4201.02   28.68 4364.18   28.34  4574.7   28.45
 4703.26   28.91    4848   28.44  4875.1   29.03 4929.93   29.12 4964.75   28.56
 4976.67   23.79    4982      17    4998      17 4998.15   21.21 5010.06   25.74
  5017.3   27.91 5030.98   28.76    5114   29.13 5262.74   29.12 5532.56   27.58
 5549.98      28 5760.16   29.29 5925.08   28.75  6377.5   29.27 6532.88   28.66
#Mann= 4 ,-1 , 0
 3246.96     .15       0 4364.18     .07       0 4964.75    .015       0
 5030.98     .15       0
#XS Ineff= 2 , 0
       0    4978   27.26    5001       0   27.26
Permanent Ineff=
       T       T
#Block Obstruct= 1 ,-1
  5469.6 5586.43      28
Bank Sta=4964.75,5030.98
XS Rating Curve= 0 ,0
Exp/Cntr=0.5,0.3

Type RM Length L Ch R = 2 ,19367   ,,,
BEGIN DESCRIPTION:
Culverts at East X Street
END DESCRIPTION:
Bridge Culvert--1,0,-1,-1, 0
Deck Dist Width WeirC Skew NumUp NumDn MinLoCord MaxHiCord MaxSubmerge Is_Ogee
70,4,2.6,0, 17, 17, , , 0.95, 0, 0,0,,
    3260    4645    4824    4878    4926    4962    4962    4973    4992    5015
    5027    5027    5070    5123    5180    5388    6500
    30.2   28.36   28.15      28   27.91   27.82   28.26   28.26   28.26   28.26
   28.26   27.89   27.89      28   28.12   27.93   28.67
       0       0       0       0       0       0       0       0       0       0
       0       0       0       0       0       0       0
    3260    4645    4824    4878    4926    4962    4962    4973    4992    5015
    5027    5027    5070    5123    5180    5388    6500
    30.2   28.36   28.15      28   27.91   27.82   28.26   28.26   28.26   28.26
   28.26   27.89   27.89      28   28.12   27.93   28.67
       0       0       0       0       0       0       0       0       0       0
       0       0       0       0       0       0       0
BR Coef=-1 , 0 , 0 ,, 0 ,,,0.8,-1,,0,
WSPro=,,,, 1 ,,,, 0 ,,,, 0 ,,,,-1 ,-1 ,-1 , 0 , 0 , 0 , 0 , 0
Culvert=2,7,6.83,70,0.012,0.5,1,10,1,17.09,4986.1,17.04,4991.1,Culvert #1  , 0 ,4
Culvert Bottom n=0.012
Culvert=2,7,6.83,70,0.012,0.5,1,10,1,17.13,4993.9,17.09,4998.9,Culvert #2  , 0 ,4
Culvert Bottom n=0.012
BC Design=,, 0 ,, 0 ,,,,,,
BC HTab HWMax=27
BC HTab MaxFlow=1000
BC Use User HTab Curves=0
BC User HTab FreeFlow(D)= 0

Type RM Length L Ch R = 1 ,19326.06,80.1,80.46,80.11
BEGIN DESCRIPTION:
East X Street
END DESCRIPTION:
XS GIS Cut Line= 6
     3198912.808    13820578.775     3200331.505    13820651.035
     3200634.496    13820666.952     3200696.409    13820666.277
     3200970.012    13820680.972     3202195.432    13820734.955
#Sta/Elev= 30
 3254.88    30.2 3341.02   29.04 3529.38   30.11 3890.72   28.95 4068.26   29.43
 4200.58   28.55 4263.58    29.4 4846.94   28.65    4913   29.23 4969.75   28.56
 4981.67   23.79    4986      17    5003      17 5003.15   21.21 5015.06   25.74
  5022.3   27.91 5035.98   28.76 5112.94   28.72 5185.74   29.78 5240.66   28.35
 5296.86   27.99 5478.64   28.46  5571.8   28.06    5705   28.97 6060.44   29.33
 6297.88   28.74 6411.66   29.35 6447.24   28.87 6475.16   29.44 6541.36   28.42
#Mann= 3 ,-1 , 0
 3254.88     .15       0 4969.75    .015       0 5035.98     .15       0
#XS Ineff= 2 , 0
       0    4984   27.26    5006       0   27.26
Permanent Ineff=
       T       T
Bank Sta=4969.75,5035.98
XS Rating Curve= 0 ,0
Exp/Cntr=0.5,0.3

Type RM Length L Ch R = 1 ,19245.6 ,1698.88,1691.92,1711.63
BEGIN DESCRIPTION:
East X Street
END DESCRIPTION:
XS GIS Cut Line= 6
     3198908.738    13820658.671     3200327.372    13820730.928
     3200632.831    13820746.975     3200694.698    13820746.301
     3200966.107    13820760.877     3202191.912    13820814.878
#Sta/Elev= 30
 3261.16   29.97 3363.42   28.63    3615   29.74 3757.64   27.35  3799.7   28.99
  4059.5   29.67 4098.78   29.11 4130.74   29.68 4220.86   28.42    4306   29.42
 4420.94   29.62  4858.1   29.45 4974.75   28.56 4986.67   23.79 4993.99    17.2
 5007.89   17.59 5008.08   17.18 5008.15   21.21 5020.06   25.74  5027.3   27.91
 5040.98   28.76    5087   29.73  5171.6   30.12  5273.6   28.47 5409.46   29.68
 5611.58   28.52 5727.56   29.53 6353.56      30 6473.38   29.88 6548.18   28.38
#Mann= 3 ,-1 , 0
 3261.16     .15       0 4974.75    .015       0 5040.98     .15       0
Bank Sta=4974.75,5040.98
XS Rating Curve= 0 ,0
Exp/Cntr=0.3,0.1

Type RM Length L Ch R = 1 ,17553.68,20.11,20.03,21.01
BEGIN DESCRIPTION:
East 13 Street
END DESCRIPTION:
XS GIS Cut Line= 6
      3198789.54    13822335.044     3199685.572    13822396.876
     3200305.984     13822425.07     3200524.224    13822433.797
      3200593.32    13822439.007     3202159.877     13822517.84
#Sta/Elev= 30
  3226.2   27.47 3539.58   26.75 3599.08    28.2 3689.38    26.6 4158.94   25.75
 4307.52    25.8  4409.5   27.08 4435.76   25.91  4604.9   26.21 4740.14   27.29
 4826.12   25.37 4881.16   27.36    4968   26.81  4993.1   18.39 4993.17   14.69
 5010.13   14.41 5020.37   22.03 5029.59   25.78 5043.21   26.73    5160   27.64
  5282.3   26.81 5682.74   27.58  5762.9    26.1 5879.74   28.26 6048.26   28.48
 6183.44   26.99  6243.8   28.31 6417.58    28.8 6518.06   26.77 6601.66   27.68
#Mann= 3 ,-1 , 0
  3226.2     .15       0    4968    .015       0 5043.21     .15       0
#Block Obstruct= 2 ,-1
 3218.43 4915.81    27.2 5703.07 5957.91    27.2
Bank Sta=4968,5043.21
XS Rating Curve= 0 ,0
Exp/Cntr=0.5,0.3

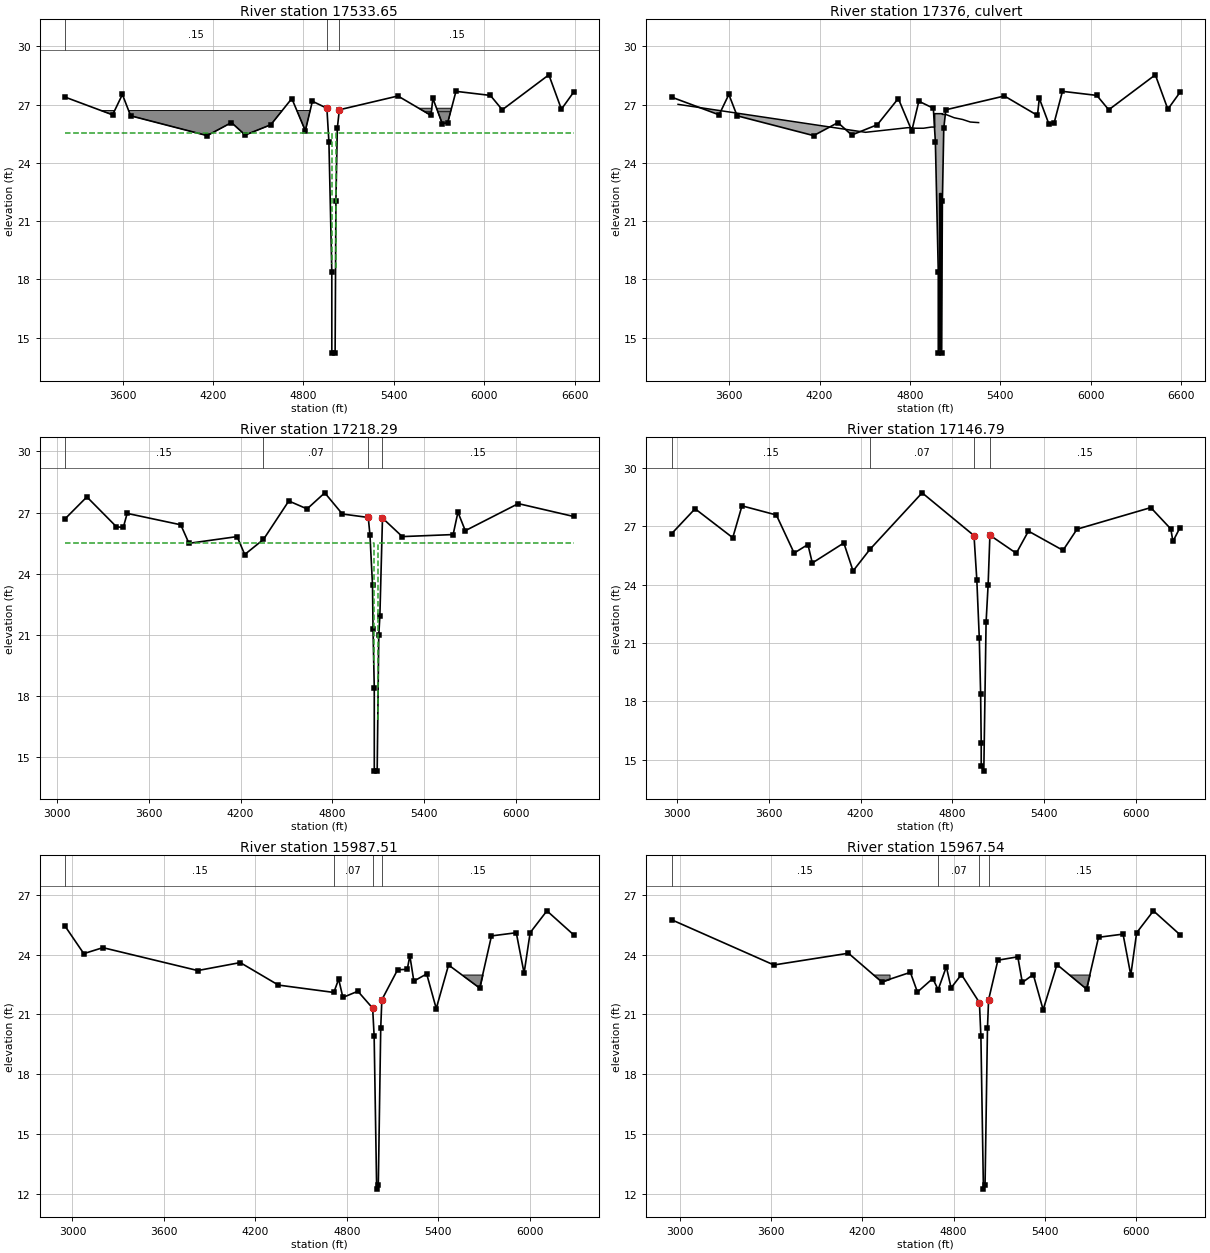
Type RM Length L Ch R = 1 ,17533.65,83.14,315.36,76.84
BEGIN DESCRIPTION:
East 13 Street
END DESCRIPTION:
XS GIS Cut Line= 6
     3198788.163    13822354.997     3199684.429    13822416.845
     3200305.131    13822445.052     3200523.072    13822453.767
     3200592.065    13822458.969     3202158.872    13822537.815
#Sta/Elev= 30
 3217.56   27.38 3532.33   26.47 3597.33   27.52 3652.09   26.42 4160.45    25.4
 4321.63   26.07 4413.03   25.43  4583.1   25.96 4722.48   27.31 4812.26   25.65
 4859.05   27.17 4955.41   26.81 4968.85   25.07  4988.1   18.39 4988.17    14.2
    5010    14.2 5015.37   22.03 5024.59   25.78 5038.21   26.73 5427.21   27.44
 5646.83   26.44 5659.07   27.32 5722.02   26.01  5757.6   26.06 5812.66   27.68
 6041.01   27.47 6120.07   26.73 6429.49   28.53 6512.82   26.76 6593.39   27.63
#Mann= 3 ,-1 , 0
 3217.56     .15       0 4955.41    .015       0 5038.21     .15       0
#XS Ineff= 2 , 0
       0    4987   25.53    5013       0   25.53
Permanent Ineff=
       T       T
#Block Obstruct= 3 ,-1
 3241.18 4870.31   26.69 5554.48 5828.55   26.81 5584.76 6208.19   26.63
Bank Sta=4955.41,5038.21
XS Rating Curve= 0 ,0
Exp/Cntr=0.5,0.3

Type RM Length L Ch R = 2 ,17376   ,,,
BEGIN DESCRIPTION:
Culverts at East 13 Street
END DESCRIPTION:
Bridge Culvert--1,0,-1,-1, 0
Deck Dist Width WeirC Skew NumUp NumDn MinLoCord MaxHiCord MaxSubmerge Is_Ogee
5,304,2.6,0, 15, 15, , , 0.95, 0, 0,0,,
    3260    4505    4787    4840    4890    4942    4964    4964    5016    5016
    5038    5094    5150    5201    5256
   27.01   25.57   25.81   25.78   25.78   25.84   25.84   26.53   26.53   26.49
   26.49   26.32   26.23    26.1   26.07
       0       0       0       0       0       0       0       0       0       0
       0       0       0       0       0
    3340    4585    4867    4920    4970    5022    5044    5044    5096    5096
    5118    5174    5230    5281    5336
   27.01   25.57   25.81   25.78   25.78   25.84   25.84   26.53   26.53   26.49
   26.49   26.32   26.23    26.1   26.07
       0       0       0       0       0       0       0       0       0       0
       0       0       0       0       0
BR Coef=-1 , 0 , 0 ,, 0 ,,,0.8,-1,,0,
WSPro=,,,, 1 ,,,, 0 ,,,, 0 ,,,,-1 ,-1 ,-1 , 0 , 0 , 0 , 0 , 0
Culvert=2,8,8,304,0.012,0.5,1,10,1,14.43,4995.2,14.34,5078.3,Culvert #1  , 0 ,5
Culvert Bottom n=0.012
Culvert=2,8,8,304,0.012,0.5,1,10,1,14.43,5004.8,14.34,5087.4,Culvert #2  , 0 ,5
Culvert Bottom n=0.012
BC Design=,, 0 ,, 0 ,,,,,,
BC HTab HWMax=27
BC HTab MaxFlow=1500
BC Use User HTab Curves=0
BC User HTab FreeFlow(D)= 0

Type RM Length L Ch R = 1 ,17218.29,76.48,71.5,80.5
BEGIN DESCRIPTION:
East 13 Street
END DESCRIPTION:
XS GIS Cut Line= 6
     3198808.839    13822447.567     3199955.811    13822514.132
     3200823.233    13822547.818     3200901.409    13822549.481
     3201211.313    13822561.755     3202124.544    13822621.829
#Sta/Elev= 30
 3054.18    26.7 3195.68   27.77 3389.14    26.3  3433.7   26.27 3458.86   26.96
 3809.08    26.4 3862.58   25.49 4177.16   25.82 4226.82   24.94 4349.18   25.68
 4514.74   27.57 4634.16   27.18 4749.56   27.97 4864.52   26.93  5033.8   26.76
  5044.8   25.91  5061.6   23.44 5064.96   21.28  5073.1   18.39 5073.17    14.3
    5092    14.3  5102.6      21 5109.59    21.9  5126.7   26.73  5256.1   25.82
 5588.24   25.92 5619.64   27.02  5667.6   26.11 6013.84   27.44  6374.7   26.81
#Mann= 4 ,-1 , 0
 3054.18     .15       0 4349.18     .07       0  5033.8    .015       0
  5126.7     .15       0
#XS Ineff= 2 , 0
       0    5070   25.53    5096       0   25.53
Permanent Ineff=
       T       T
Bank Sta=5033.8,5126.7
XS Rating Curve= 0 ,0
Exp/Cntr=0.5,0.3

Type RM Length L Ch R = 1 ,17146.79,1147.94,1159.28,1155.8
BEGIN DESCRIPTION:
East 13 Street
END DESCRIPTION:
XS GIS Cut Line= 6
     3198804.204    13822527.433       3199952.4    13822594.069
     3200828.163    13822618.012     3200843.276    13822618.576
     3201206.156    13822641.589     3202119.292    13822701.656
#Sta/Elev= 30
 2966.46   26.63 3119.26   27.91 3365.38   26.42 3425.68   28.06 3650.14   27.59
 3766.26   25.63 3856.34   26.07 3885.05   25.12 4090.84   26.15 4151.14   24.71
 4261.28   25.82 4602.27   28.73  4941.1   26.53  4959.4   24.26  4975.5   21.28
  4984.3   18.39 4988.14   15.88 4988.17   14.69 5005.13   14.41    5020   22.07
  5033.3      24    5045   26.55 5217.19   25.62 5296.62   26.76 5522.49   25.77
 5613.95   26.86 6095.74   27.97  6226.6   26.87 6240.31   26.23 6286.52   26.94
#Mann= 4 ,-1 , 0
 2966.46     .15       0 4261.28     .07       0  4941.1    .015       0
    5045     .15       0
Bank Sta=4941.1,5045
XS Rating Curve= 0 ,0
Exp/Cntr=0.3,0.1

Type RM Length L Ch R = 1 ,15987.51,20.01,19.97,19.94
BEGIN DESCRIPTION:
9th Street
END DESCRIPTION:
XS GIS Cut Line= 6
      3198725.43    13823683.249     3199771.945    13823727.928
     3200545.326    13823760.194     3200750.728    13823774.601
      3200802.41    13823777.666 3202058.394480513823808.1407855
#Sta/Elev= 30
 2952.45   25.42 3074.31   24.05 3199.79   24.35 3822.11    23.2 4100.96    23.6
 4351.38   22.47 4715.18    22.1 4746.84   22.77 4774.45   21.85 4872.77   22.16
 4969.87   21.31 4979.64    19.9 4996.21   12.22 5006.97   12.43 5022.86   20.31
 5030.13   21.73 5133.74   23.24 5197.08   23.26 5213.84   23.95 5240.08   22.67
 5324.48   23.03 5387.06   21.29 5467.92   23.48 5672.16   22.32 5749.56   24.94
 5912.22    25.1 5963.56   23.07  6003.2    25.1  6113.4    26.2    6288      25
#Mann= 4 ,-1 , 0
 2952.45     .15       0 4715.18     .07       0 4969.87    .015       0
 5030.13     .15       0
#XS Ineff= 1 ,-1
 5207.62 5470.42   23.15
Permanent Ineff=
       T
#Block Obstruct= 1 ,-1
 5562.56 5730.79      23
Bank Sta=4969.87,5030.13
XS Rating Curve= 0 ,0
Exp/Cntr=0.5,0.3

Type RM Length L Ch R = 1 ,15967.54,25.02,25.58,25.83
BEGIN DESCRIPTION:
9th Street
END DESCRIPTION:
XS GIS Cut Line= 6
      3198717.81    13823707.155     3199776.547    13823748.137
     3200544.209    13823780.165     3200748.211    13823794.474
     3200800.909    13823797.553 3202055.749684213823828.1115878
#Sta/Elev= 30
 2947.64   25.75 3619.47   23.48 4109.32   24.07 4327.68   22.63 4516.08   23.11
 4562.56   22.12 4663.22    22.8 4698.68   22.24 4752.48   23.39  4783.8   22.33
  4851.7      23 4969.87   21.59 4979.64    19.9 4996.21   12.22 5006.97   12.43
 5022.86   20.31 5030.13   21.73 5091.32   23.72 5222.14   23.89 5251.78    22.6
 5323.86      23 5388.66   21.23 5479.62    23.5 5673.74   22.27 5752.58   24.87
 5913.82   25.03 5964.62   22.97  6003.2    25.1  6113.4    26.2    6288      25
#Mann= 4 ,-1 , 0
 2947.64     .15       0 4698.68     .07       0 4969.87    .015       0
 5030.13     .15       0
#XS Ineff= 3 ,-1
 2947.64 4969.87   21.59 5030.13    5100   21.73 5187.71 5490.33   23.21
Permanent Ineff=
       T       T       T
#Block Obstruct= 2 ,-1
 4216.15 4379.41      23 5526.17 5749.15      23
Bank Sta=4969.87,5030.13
XS Rating Curve= 0 ,0
Exp/Cntr=0.5,0.3

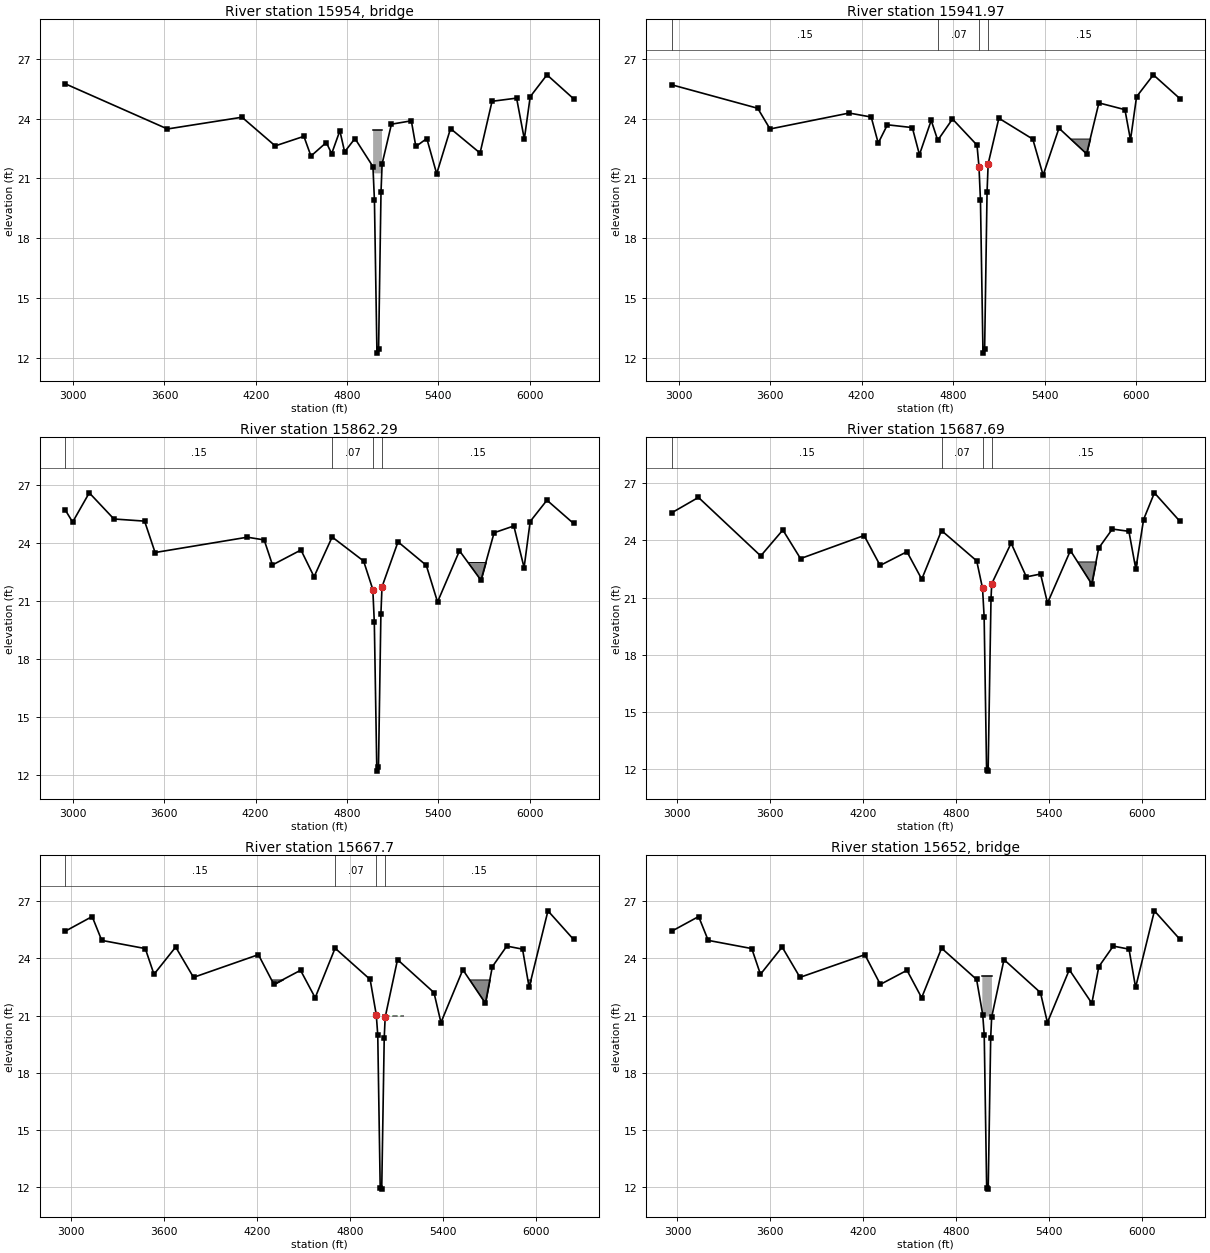
Type RM Length L Ch R = 3 ,15954   ,,,
BEGIN DESCRIPTION:
Footbridge at 9th Street
END DESCRIPTION:
Bridge Culvert--1,0,-1,-1, 0
Deck Dist Width WeirC Skew NumUp NumDn MinLoCord MaxHiCord MaxSubmerge Is_Ogee
4,12,2.6,0, 2, 2, , , 0.95, 0, 0,0,,
    4971    5029
   23.43   23.43
   21.25   21.25
    4971    5029
   23.43   23.43
   21.25   21.25
BR Coef=-1 , 1 , 0 ,, 0 ,,,0.8,-1,2,0,
WSPro=,,,, 1 ,,,, 0 ,,,, 0 ,,,,-1 ,-1 ,-1 , 0 , 0 , 0 , 0 , 0
BC Design=,, 0 ,, 0 ,,,,,,
BC HTab HWMax=26.2
BC HTab MaxFlow=1500
BC Use User HTab Curves=0
BC User HTab FreeFlow(D)= 0

Type RM Length L Ch R = 1 ,15941.97,80.06,79.68,79.47
BEGIN DESCRIPTION:
9th Street
END DESCRIPTION:
XS GIS Cut Line= 6
      3198723.74    13823730.885     3199776.864    13823773.172
     3200542.813    13823805.129     3200745.064    13823819.315
     3200796.193    13823823.672 3202054.287703113823852.6621949
#Sta/Elev= 30
 2954.93    25.7 3519.01   24.52 3599.85   23.48  4118.6   24.28 4263.21   24.08
 4309.27   22.77 4369.33   23.69 4532.76   23.55 4579.51   22.19 4656.71   23.91
 4699.61   22.91 4796.23   23.98  4956.9   22.67 4969.87   21.59 4979.64    19.9
 4996.21   12.22 5006.97   12.43 5022.86   20.31 5030.13   21.73 5100.33   24.02
 5322.79   22.97 5390.46   21.16 5494.38   23.52 5675.53   22.23 5756.19   24.79
 5926.98   24.45 5963.29   22.93  6003.2    25.1  6113.4    26.2    6288      25
#Mann= 4 ,-1 , 0
 2954.93     .15       0 4699.61     .07       0 4969.87    .015       0
 5030.13     .15       0
#XS Ineff= 4 ,-1
 4534.01 4626.84      23    4700 4969.87   21.59 5030.13    5100   21.73
  5211.6 5498.29   23.05
Permanent Ineff=
       T       T       T       T
#Block Obstruct= 1 ,-1
    5550    5700      23
Bank Sta=4969.87,5030.13
XS Rating Curve= 0 ,0
Exp/Cntr=0.5,0.3

Type RM Length L Ch R = 1 ,15862.29,179.78,174.6,171.84
BEGIN DESCRIPTION:
9th Street
END DESCRIPTION:
XS GIS Cut Line= 6
      3198714.93     13823797.67     3199778.556    13823853.312
     3200538.346    13823885.012     3200734.994    13823898.805
     3200791.837      13823902.8 3202050.219054713823932.8575337
#Sta/Elev= 30
 2949.62    25.7 2998.31   25.07 3107.61   26.58 3269.52   25.23 3470.93   25.12
 3539.86    23.5 4145.55   24.29 4256.26   24.15  4310.8   22.86 4497.93   23.63
 4583.94   22.25 4702.72    24.3 4909.34   23.06 4969.87   21.59 4979.64    19.9
 4996.21   12.22 5006.97   12.43 5022.86   20.31 5030.13   21.73 5135.28   24.05
 5320.91   22.84 5394.83   20.95 5539.06   23.59 5679.91   22.07 5766.28   24.52
 5895.92   24.87 5963.31   22.72  6003.2    25.1  6113.4    26.2    6288      25
#Mann= 4 ,-1 , 0
 2949.62     .15       0 4702.72     .07       0 4969.87    .015       0
 5030.13     .15       0
#XS Ineff= 2 ,-1
 4513.56 4650.64      23 5195.68 5538.11   22.99
Permanent Ineff=
       T       T
#Block Obstruct= 1 ,-1
    5550    5800   23.01
Bank Sta=4969.87,5030.13
XS Rating Curve= 0 ,0
Exp/Cntr=0.3,0.1

Type RM Length L Ch R = 1 ,15687.69,20.02,19.99,20.01
BEGIN DESCRIPTION:
Footbridge
END DESCRIPTION:
XS GIS Cut Line= 6
      3198716.48    13823993.686     3199815.034    13824033.618
     3200551.101    13824066.099     3200876.675    13824080.592
 3201895.876201313824086.1364103 3201995.8747217 13824086.680398
#Sta/Elev= 30
 2964.23   25.45 3136.94   26.26 3539.03   23.19 3681.89   24.55  3795.9   23.05
 4206.26   24.26 4309.84   22.69 4482.98   23.41 4578.46   21.97 4706.08   24.52
  4933.1   22.93 4970.86   21.49 4981.14   19.99 4996.92   11.97 5006.81    11.9
  5025.4   20.92    5030   21.73  5155.3   23.86 5253.68   22.09 5345.24   22.24
 5390.22   20.72 5538.14   23.47 5675.64   21.71 5720.64    23.6 5808.82    24.6
 5915.64   24.48 5960.21    22.5  6010.3    25.1  6080.2    26.5  6245.4      25
#Mann= 4 ,-1 , 0
 2964.23     .15       0 4706.08     .07       0 4970.86    .015       0
    5030     .15       0
#XS Ineff= 2 ,-1
 4495.57 4646.38      23 5183.73 5546.08      23
Permanent Ineff=
       T       T
#Block Obstruct= 2 ,-1
    5550    5800    22.9    5900    6000    22.9
Bank Sta=4970.86,5030
XS Rating Curve= 0 ,0
Exp/Cntr=0.5,0.3

Type RM Length L Ch R = 1 ,15667.7 ,30.03,29.98,30.01
BEGIN DESCRIPTION:
Footbridge
END DESCRIPTION:
XS GIS Cut Line= 6
      3198716.48    13824014.581     3199811.962    13824053.502
     3200549.902    13824086.066     3200876.678    13824100.592
      3201710.58    13824105.129 3201997.305736813824106.6889851
#Sta/Elev= 30
 2962.83   25.43 3136.92    26.2 3198.68   24.95 3480.05   24.52 3536.16   23.17
 3676.21    24.6 3791.38   23.01 4210.43    24.2 4310.34   22.64 4482.48   23.38
 4577.05   21.94 4705.71   24.54 4931.87    22.9  4971.5   21.05 4981.14   19.99
 4996.92   11.97 5006.81    11.9 5022.95   19.85 5029.14   20.92 5108.82   23.94
  5344.2   22.21 5389.18   20.64 5530.66   23.41 5676.14   21.65 5721.14   23.57
 5814.33   24.65 5916.15   24.49 5958.67   22.48  6080.2    26.5  6245.4      25
#Mann= 4 ,-1 , 0
 2962.83     .15       0 4705.71     .07       0  4971.5    .015       0
 5029.14     .15       0
#XS Ineff= 4 ,-1
 4474.97 4670.08   22.96    4800  4971.5   21.05    5030    5150      21
 5187.71 5538.11      23
Permanent Ineff=
       T       T       T       T
#Block Obstruct= 3 ,-1
 4244.03  4403.3    22.9    5550 5769.06    22.9    5900    6000    22.9
Bank Sta=4971.5,5029.14
XS Rating Curve= 0 ,0
Exp/Cntr=0.5,0.3

Type RM Length L Ch R = 3 ,15652   ,,,
BEGIN DESCRIPTION:
Footbridge
END DESCRIPTION:
Bridge Culvert--1,0,-1,-1, 0
Deck Dist Width WeirC Skew NumUp NumDn MinLoCord MaxHiCord MaxSubmerge Is_Ogee
4,12,2.6,0, 2, 2, , , 0.95, 0, 0,0,,
    4969    5031
    23.1    23.1
   20.98   20.98
    4969    5031
    23.1    23.1
   20.98   20.98
BR Coef=-1 , 1 , 0 ,, 0 ,,,0.8,-1,2,0,
WSPro=,,,, 1 ,,,, 0 ,,,, 0 ,,,,-1 ,-1 ,-1 , 0 , 0 , 0 , 0 , 0
BC Design=,, 0 ,, 0 ,,,,,,
BC HTab HWMax=26.5
BC HTab MaxFlow=2000
BC Use User HTab Curves=0
BC User HTab FreeFlow(D)= 0