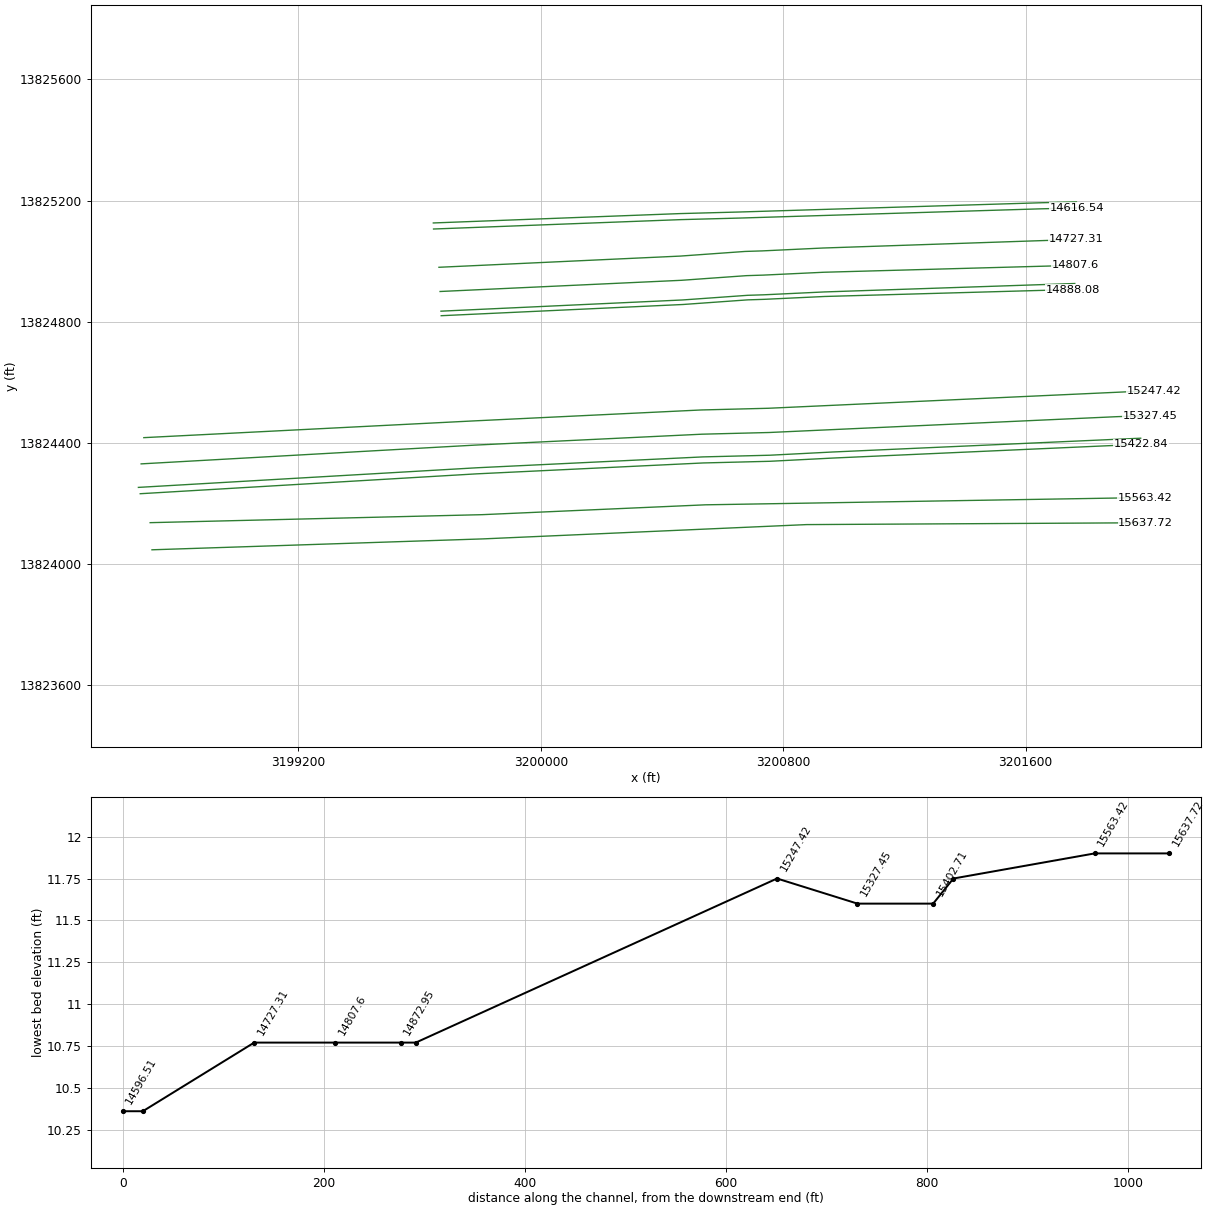
HEC-RAS study G104-00-00.prj: G104-00-00

--- G104-00-00.g01 (geometry) --- (continued)

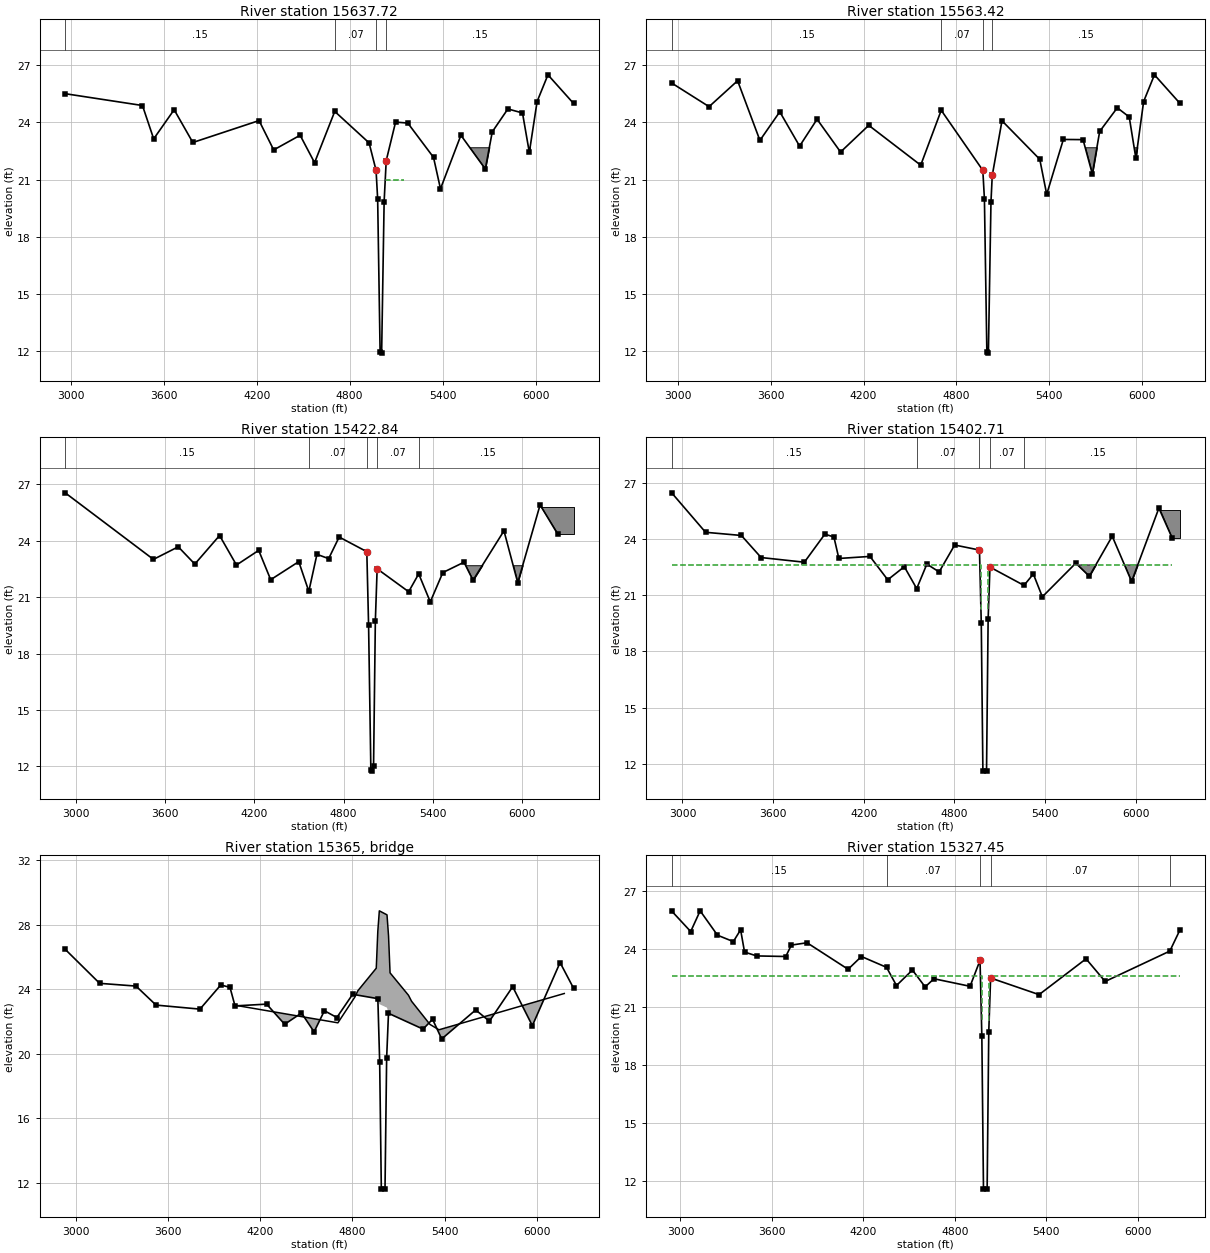
Type RM Length L Ch R = 1 ,15637.72,80.07,74.3,73.1
BEGIN DESCRIPTION:
Footbridge
END DESCRIPTION:
XS GIS Cut Line= 6
      3198716.48    13824047.415     3199808.975    13824083.399
     3200548.104    13824116.016     3200876.683    13824130.592
     3201710.417    13824135.128 3201995.732601613824136.6802835
#Sta/Elev= 30
  2964.5   25.51 3463.13   24.89 3535.54   23.14  3667.6   24.67 3788.28   22.95
 4215.72    24.1 4310.12   22.56 4480.76   23.33 4573.99   21.89 4704.18   24.58
  4925.8   22.93 4970.86   21.49 4981.14   19.99 4996.92   11.97 5006.81    11.9
 5022.95   19.85  5036.4      22  5096.8   24.02 5175.63   23.97 5341.68   22.17
 5386.66   20.52 5518.47   23.33 5675.92   21.56 5720.93   23.51 5821.62   24.71
 5915.93    24.5 5960.08   22.43  6010.3    25.1  6080.2    26.5  6245.4      25
#Mann= 4 ,-1 , 0
  2964.5     .15       0 4704.18     .07       0 4970.86    .015       0
  5036.4     .15       0
#XS Ineff= 4 ,-1
 4455.06 4670.08      23    4800 4970.86   21.49    5030    5150      21
 5203.64 5538.11      23
Permanent Ineff=
       T       T       T       T
#Block Obstruct= 2 ,-1
    5550 5788.96    22.7    5900    6000    22.7
Bank Sta=4970.86,5036.4
XS Rating Curve= 0 ,0
Exp/Cntr=0.5,0.3

Type RM Length L Ch R = 1 ,15563.42,137.19,140.58,150.63
BEGIN DESCRIPTION:
Footbridge
END DESCRIPTION:
XS GIS Cut Line= 5
      3198710.51    13824136.965     3199806.019    13824163.346
      3200543.31    13824195.882     3201709.982    13824215.127
 3201995.133148413824219.8307504
#Sta/Elev= 30
 2959.55   26.07 3201.29   24.83 3385.72   26.19 3529.98   23.06 3658.33   24.56
 3786.46   22.76 3899.34   24.17 4051.28   22.45 4233.46   23.85 4569.42   21.76
 4701.94   24.64 4970.86   21.49 4981.14   19.99 4996.92   11.97 5006.81    11.9
  5023.6   19.85  5031.8   21.22  5094.7   24.09 5338.84   22.07 5383.78   20.23
  5491.4   23.11 5618.74    23.1 5678.74    21.3  5726.2   23.53 5839.96   24.77
 5917.18   24.29 5960.21   22.12  6010.3    25.1  6080.2    26.5  6245.4      25
#Mann= 4 ,-1 , 0
 2959.55     .15       0 4701.94     .07       0 4970.86    .015       0
  5031.8     .15       0
#XS Ineff= 2 ,-1
 4232.08 4686.01   22.76 5171.79 5502.28   22.83
Permanent Ineff=
       T       T
#Block Obstruct= 2 ,-1
    5550 5784.98    22.7    5900    6050    22.7
Bank Sta=4970.86,5031.8
XS Rating Curve= 0 ,0
Exp/Cntr=0.3,0.1

Type RM Length L Ch R = 1 ,15422.84,20.01,20.13,20
BEGIN DESCRIPTION:
8th Street
END DESCRIPTION:
XS GIS Cut Line= 6
      3198677.67    13824232.484     3199787.948    13824298.074
     3200535.419    13824334.023     3200756.086    13824339.547
     3200964.003    13824350.213     3201980.452    13824395.762
#Sta/Elev= 30
 2929.85   26.55 3522.31   23.01 3689.04   23.68 3800.17   22.76 3966.55   24.28
 4079.92   22.71  4229.3   23.49 4309.76   21.93 4498.26   22.89 4565.88   21.31
 4620.44   23.28 4699.06   23.05  4769.6    24.2 4955.33   23.42 4967.22   19.51
 4982.52   11.81 4990.86   11.75 5000.58      12 5012.63   19.73 5024.67   22.51
 5236.34   21.29 5303.84   22.24 5381.48   20.75 5465.82   22.31 5608.08   22.86
 5668.58    21.9 5876.38   24.53 5968.88   21.77 6119.02   25.91  6236.8   24.36
#Mann= 5 ,-1 , 0
 2929.85     .15       0 4565.88     .07       0 4955.33    .015       0
 5024.67     .07       0 5303.84     .15       0
#XS Ineff= 1 ,-1
 4206.48  4684.3   22.86
Permanent Ineff=
       T
#Block Obstruct= 3 ,-1
 5603.53  5735.5    22.7 5890.22 6094.99    22.7 6118.89 6343.57   25.82
Bank Sta=4955.33,5024.67
XS Rating Curve= 0 ,0
Exp/Cntr=0.5,0.3

Type RM Length L Ch R = 1 ,15402.71,75.06,75.26,74.94
BEGIN DESCRIPTION:
8th Street
END DESCRIPTION:
XS GIS Cut Line= 6
       3198671.7    13824253.378     3199791.111    13824318.249
     3200534.628    13824354.008     3200755.553    13824359.546
     3200963.043     13824370.19     3201979.556    13824415.742
#Sta/Elev= 30
 2928.37   26.48 3152.71   24.37 3389.62    24.2 3520.22   23.02 3806.46   22.77
 3942.01   24.27 4001.99   24.12 4034.72   22.97 4240.62   23.08 4358.22   21.83
 4467.88   22.53 4549.92   21.36 4617.22   22.67 4698.24   22.25 4801.12   23.69
 4965.33   23.42 4977.22   19.51    4988    11.6    5012    11.6 5022.63   19.73
 5034.67   22.51 5259.88   21.53 5321.82   22.14 5381.32   20.92  5602.8   22.72
 5692.24   22.02 5843.86   24.16 5972.02   21.74 6152.58   25.66 6240.33   24.07
#Mann= 5 ,-1 , 0
 2928.37     .15       0 4549.92     .07       0 4965.33    .015       0
 5034.67     .07       0 5259.88     .15       0
#XS Ineff= 2 , 0
       0    4975   22.61    5025       0   22.61
Permanent Ineff=
       T       T
#Block Obstruct= 3 ,-1
 5598.98 5785.55   22.65 5853.81  6158.7   22.65 6153.01 6292.38   25.55
Bank Sta=4965.33,5034.67
XS Rating Curve= 0 ,0
Exp/Cntr=0.5,0.3

Type RM Length L Ch R = 3 ,15365   ,,,
BEGIN DESCRIPTION:
New Bridge at 8th Street
END DESCRIPTION:
Bridge Culvert--1,0,-1,-1, 0
Deck Dist Width WeirC Skew NumUp NumDn MinLoCord MaxHiCord MaxSubmerge Is_Ogee
7,52,2.6,0, 17, 17, , , 0.95, 0, 0,0,,
    4042    4705    4815    4835    4955    4965    4975    5000    5025    5035
    5045    5165    5185    5305    53355363.608    6180
      23   21.92   23.51   23.91   25.31   27.59   28.87  28.745   28.62   27.32
   25.02   23.63   23.26   21.82   21.6521.48788   23.74
       0       0       0       0       0       0   23.08   22.97   22.86       0
       0       0       0       0
    4042    4705    4815    4835    4955    4965    4975    5000    5025    5035
    5045    5165    5185    5305    53355363.608    6180
      23   21.92   23.51   23.91   25.31   27.59   28.87  28.745   28.62   27.32
   25.02   23.63   23.26   21.82   21.6521.48788   23.74
       0       0       0       0       0       0   23.08   22.97   22.86       0
       0       0       0       0
BR Coef=-1 , 0 , 0 ,, 0 ,,,0.8,-1,,0,
WSPro=,,,, 1 ,,,, 0 ,,,, 0 ,,,,-1 ,-1 ,-1 , 0 , 0 , 0 , 0 , 0
BC Design=,, 0 ,, 0 ,,,,,,
BC HTab HWMax=26.48
BC HTab MaxFlow=2000
BC Use User HTab Curves=0
BC User HTab FreeFlow(D)= 0

Type RM Length L Ch R = 1 ,15327.45,80.06,80.03,80.07
BEGIN DESCRIPTION:
8th Street
END DESCRIPTION:
XS GIS Cut Line= 6
      3198680.66    13824330.988     3199781.868    13824392.891
     3200531.663    13824428.952     3200753.553    13824434.542
     3201902.258    13824486.833     3202011.472    13824490.186
#Sta/Elev= 30
 2942.46   25.97 3067.27   24.91 3129.22   25.98 3243.07   24.72 3346.93   24.39
  3394.7      25  3420.5   23.85  3499.6   23.65 3691.05   23.62 3727.61   24.21
 3830.55   24.33 4099.75   22.96  4187.3   23.62 4352.14   23.06 4417.19   22.12
 4521.65   22.92 4605.37   22.05 4663.31   22.47    4900   22.08 4965.33   23.42
 4977.22   19.51    4988    11.6    5012    11.6 5022.63   19.73 5034.67   22.51
 5352.65   21.65 5660.86    23.5 5786.15   22.33 6210.51    23.9  6277.2      25
#Mann= 5 ,-1 , 0
 2942.46     .15       0 4352.14     .07       0 4965.33    .015       0
 5034.67     .07       0 6210.51     .15       0
#XS Ineff= 2 , 0
       0    4975   22.61    5025       0   22.61
Permanent Ineff=
       T       T
Bank Sta=4965.33,5034.67
XS Rating Curve= 0 ,0
Exp/Cntr=0.5,0.3

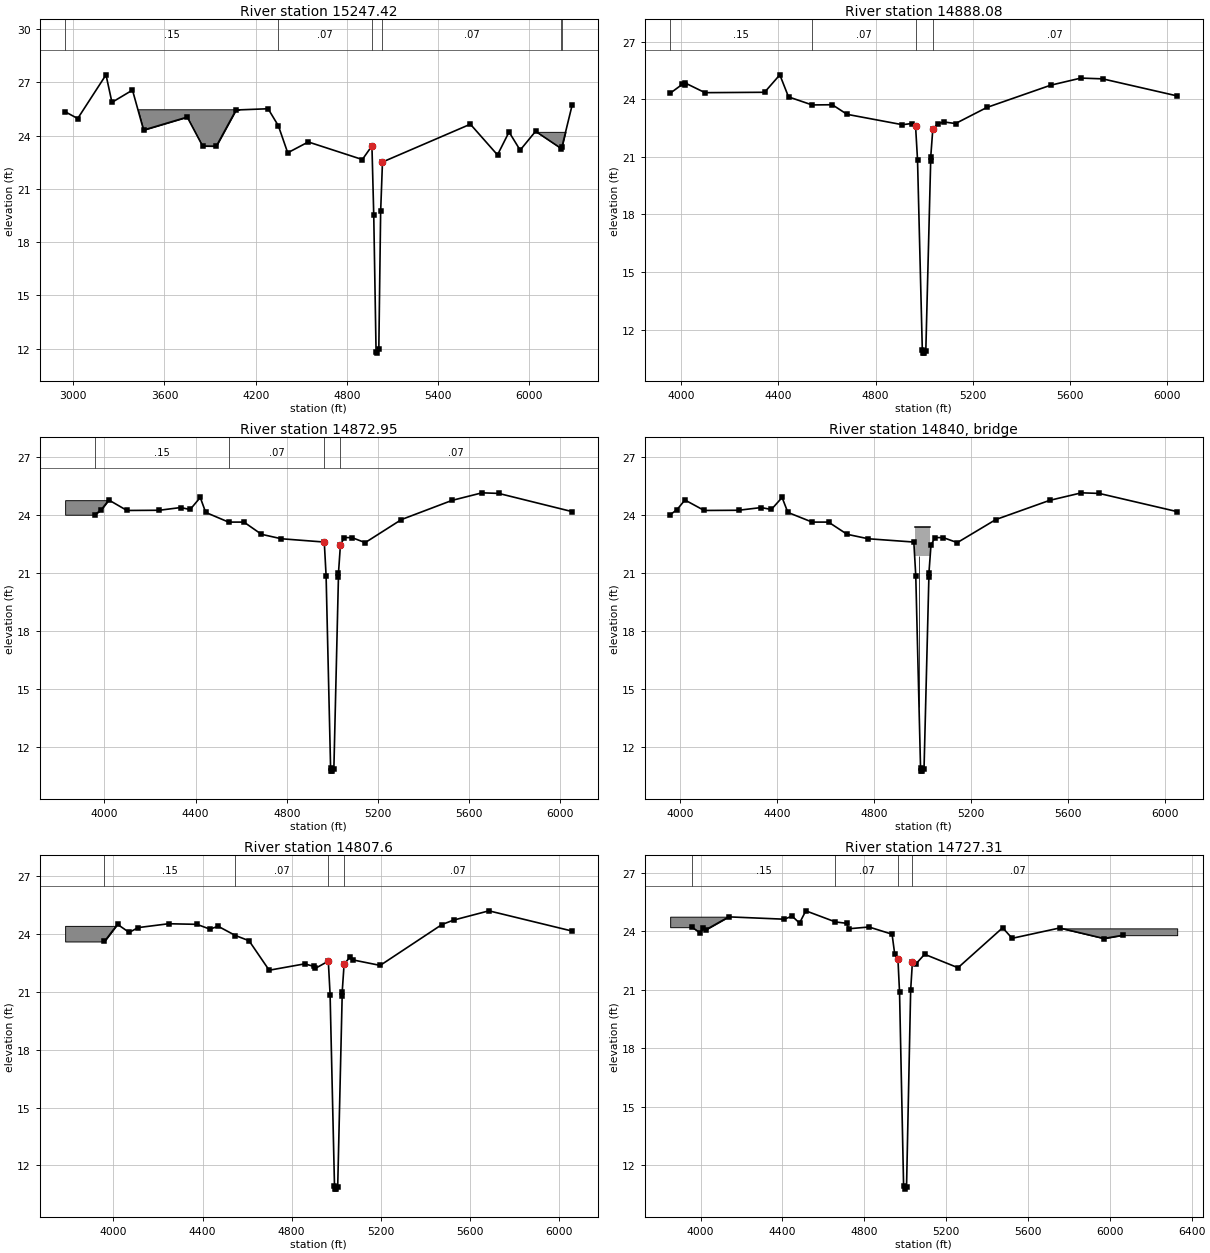
Type RM Length L Ch R = 1 ,15247.42,351.35,359.34,366.27
BEGIN DESCRIPTION:
8th Street
END DESCRIPTION:
XS GIS Cut Line= 6
      3198689.61    13824417.552     3199782.035    13824472.992
     3200528.501    13824508.893      3200751.42    13824514.538
     3201964.516    13824570.224     3202022.503    13824570.295
#Sta/Elev= 30
 2946.37   25.34 3029.05   24.96 3215.26   27.42 3254.33   25.87 3389.51   26.56
 3462.57   24.31 3749.74   25.04 3850.95   23.41 3941.09    23.4 4071.01   25.44
 4281.91   25.51 4349.55   24.55 4411.05   23.03 4546.35   23.64 4902.06   22.65
 4965.33   23.42 4977.22   19.51 4992.52   11.81 5000.86   11.75 5010.58      12
 5022.63   19.73 5034.67   22.51 5613.03   24.64 5791.59   22.91  5867.5    24.2
 5940.64   23.18 6042.23   24.24 6211.13   23.27 6216.16   23.38 6282.89   25.72
#Mann= 6 ,-1 , 0
 2946.37     .15       0 4349.55     .07       0 4965.33    .015       0
 5034.67     .07       0 6211.13     .15       0 6216.16     .15       0
#Block Obstruct= 2 ,-1
 3323.66 4092.72   25.48 6040.39 6377.13   24.21
Bank Sta=4965.33,5034.67
XS Rating Curve= 0 ,0
Exp/Cntr=0.3,0.1

Type RM Length L Ch R = 1 ,14888.08,15.01,15.13,16.68
BEGIN DESCRIPTION:
access road
END DESCRIPTION:
XS GIS Cut Line= 6
     3199671.017    13824819.992     3200469.019    13824857.008
      3200682.59    13824872.291     3200737.176    13824874.034
     3200936.329    13824883.453     3201756.429    13824906.472
#Sta/Elev= 30
 3954.22   24.32  4004.8   24.79 4014.82   24.75 4016.69   24.85 4097.59   24.35
 4342.89   24.37 4405.76   25.28 4441.42   24.13 4538.69   23.71 4621.78   23.72
 4682.52   23.22    4910   22.68    4948   22.74  4964.6   22.59 4972.55   20.86
  4992.3   10.94 4993.49   10.78 4998.01   10.77 5006.72    10.9 5026.73   20.77
 5026.85   20.98  5035.4   22.43    5056   22.74    5083   22.82    5129   22.74
 5258.23   23.58    5521   24.74  5645.2   25.11 5734.74   25.07 6041.61   24.18
#Mann= 4 ,-1 , 0
 3954.22     .15       0 4538.69     .07       0  4964.6    .015       0
  5035.4     .07       0
Bank Sta=4964.6,5035.4
XS Rating Curve= 0 ,0
Exp/Cntr=0.5,0.3

Type RM Length L Ch R = 1 ,14872.95,65.05,65.35,65.97
BEGIN DESCRIPTION:
access road
END DESCRIPTION:
XS GIS Cut Line= 6
     3199670.322    13824834.976     3200468.136    13824871.983
     3200681.815    13824887.274     3200736.582    13824889.023
     3200935.787    13824898.444     3201762.104    13824926.257
#Sta/Elev= 30
 3958.28      24 3986.29   24.26 4019.28   24.76 4098.85   24.22 4240.57   24.23
 4334.34   24.37 4376.08   24.27 4420.51   24.89 4444.31   24.12 4544.57   23.62
 4612.17   23.62 4688.96   22.99 4776.13   22.76  4964.6   22.59 4972.55   20.86
  4992.3   10.94 4993.49   10.78 4998.01   10.77 5006.72    10.9 5026.73   20.77
 5026.85   20.98  5035.4   22.43    5052   22.82    5086   22.82    5144   22.56
 5303.05   23.75 5525.16   24.74  5656.8   25.13 5729.75    25.1 6052.18   24.16
#Mann= 4 ,-1 , 0
 3958.28     .15       0 4544.57     .07       0  4964.6    .015       0
  5035.4     .07       0
#XS Ineff= 2 , 0
       0  4964.6   22.59  5035.4       0   22.43
Permanent Ineff=
       T       T
#Block Obstruct= 1 ,-1
 3827.65 4018.77   24.75
Bank Sta=4964.6,5035.4
XS Rating Curve= 0 ,0
Exp/Cntr=0.5,0.3

Type RM Length L Ch R = 3 ,14840   ,,,
BEGIN DESCRIPTION:
Bridge at access road
END DESCRIPTION:
Bridge Culvert--1,0,-1,-1, 0
Deck Dist Width WeirC Skew NumUp NumDn MinLoCord MaxHiCord MaxSubmerge Is_Ogee
5,38,2.6,0, 2, 2, , , 0.95, 0, 0,0,,
    4968    5032
   23.37   23.37
   21.89   21.89
    4968    5032
   23.37   23.37
   21.89   21.89
Pier Skew, UpSta & Num, DnSta & Num=  ,4986, 2 ,4986, 2 , 0 , 0 , 0 ,,
       3       3
       0      22
       3       3
       0      22
BR Coef=-1 , 1 , 0 ,, 0 ,,,0.8,-1,2,0,
WSPro=,,,, 1 ,,,, 0 ,,,, 0 ,,,,-1 ,-1 ,-1 , 0 , 0 , 0 , 0 , 0
BC Design=,, 0 ,, 0 ,,,,,,
BC HTab HWMax=26
BC HTab MaxFlow=2000
BC Use User HTab Curves=0
BC User HTab FreeFlow(D)= 0

Type RM Length L Ch R = 1 ,14807.6 ,80.08,80.28,84.32
BEGIN DESCRIPTION:
access road
END DESCRIPTION:
XS GIS Cut Line= 6
      3199667.31    13824899.906      3200464.31    13824936.876
     3200678.457      13824952.2     3200734.009    13824953.974
     3200933.354    13824963.402     3201764.689    13824986.324
#Sta/Elev= 30
 3959.77   23.61 4018.37    24.5  4070.7   24.08 4110.99   24.33 4247.49   24.53
 4374.48    24.5  4433.4   24.25 4469.83    24.4 4547.59   23.92 4608.73   23.65
 4699.16   22.12 4858.35   22.45 4899.72   22.32    4907   22.22  4964.6   22.59
 4972.55   20.86  4992.3   10.94 4993.49   10.78 4998.01   10.77 5006.72    10.9
 5026.73   20.77 5026.85   20.98  5035.4   22.43    5063   22.82    5077   22.65
 5197.43   22.37 5474.74   24.49 5527.18   24.72 5685.49    25.2 6059.12   24.15
#Mann= 4 ,-1 , 0
 3959.77     .15       0 4547.59     .07       0  4964.6    .015       0
  5035.4     .07       0
#XS Ineff= 2 , 0
       0  4964.6   22.59  5035.4       0   22.43
Permanent Ineff=
       T       T
#Block Obstruct= 1 ,-1
 3783.28 4022.18   24.42
Bank Sta=4964.6,5035.4
XS Rating Curve= 0 ,0
Exp/Cntr=0.5,0.3

Type RM Length L Ch R = 1 ,14727.31,122.81,110.77,110.25
BEGIN DESCRIPTION:
access road
END DESCRIPTION:
XS GIS Cut Line= 6
     3199663.603     13824979.82     3200459.601    13825016.743
     3200674.323    13825032.108     3200730.842    13825033.913
     3200930.379     13825043.35     3201767.443    13825071.684
#Sta/Elev= 30
  3958.6   24.21 3997.24   23.92 4014.26   24.18 4026.42   24.08  4137.6   24.74
 4409.62   24.62 4447.34   24.78 4483.64   24.42 4514.46   25.05 4659.14   24.48
 4713.76   24.41 4725.12   24.13 4823.14   24.22    4936   23.85    4949   22.82
  4964.6   22.59 4972.55   20.86  4992.3   10.94 4998.01   10.77 5006.72    10.9
 5026.85   20.98  5035.4   22.43    5052   22.32    5095   22.82  5258.2   22.13
 5476.32   24.18 5522.82   23.64 5755.06   24.17  5971.5   23.63 6064.58    23.8
#Mann= 4 ,-1 , 0
  3958.6     .15       0 4659.14     .07       0  4964.6    .015       0
  5035.4     .07       0
#Block Obstruct= 2 ,-1
 3851.54 4134.81   24.75  5762.8 6329.35   24.15
Bank Sta=4964.6,5035.4
XS Rating Curve= 0 ,0
Exp/Cntr=0.3,0.1

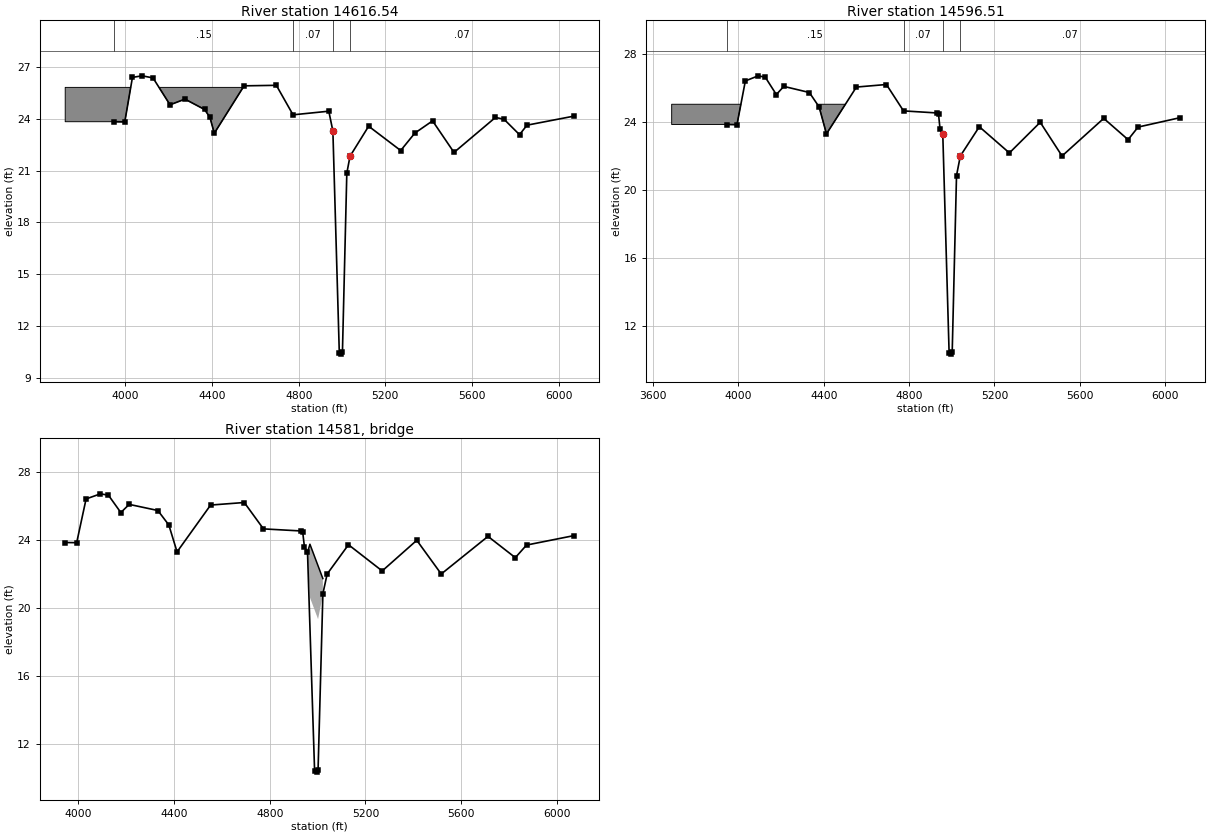
Type RM Length L Ch R = 1 ,14616.54,20.01,20.03,20.71
BEGIN DESCRIPTION:
Footbridge
END DESCRIPTION:
XS GIS Cut Line= 5
     3199645.789    13825106.116     3200461.452    13825137.078
     3200657.959    13825142.311     3201652.295    13825172.803
     3201767.839    13825175.566
#Sta/Elev= 30
 3945.82   23.83 3996.96   23.82 4032.28    26.4 4076.94   26.49 4127.24   26.37
 4205.84   24.81 4274.72   25.14 4365.14   24.54 4389.96   24.09 4410.28   23.16
 4547.82   25.91 4696.76   25.94 4773.88   24.23    4939   24.44 4957.83   23.29
 4987.47   10.44  4995.5   10.36 5001.98   10.49 5022.17   20.85    5037   21.83
    5123   23.57 5270.92   22.16 5336.26   23.17 5418.14   23.88  5517.1   22.05
  5708.7   24.08 5748.32   23.97  5819.6   23.08  5854.2   23.63 6069.04   24.15
#Mann= 4 ,-1 , 0
 3945.82     .15       0 4773.88     .07       0 4957.83    .015       0
    5037     .07       0
#Block Obstruct= 1 ,-1
 3721.84 4554.61   25.82
Bank Sta=4957.83,5037
XS Rating Curve= 0 ,0
Exp/Cntr=0.5,0.3

Type RM Length L Ch R = 1 ,14596.51,30.02,31.19,31.9
BEGIN DESCRIPTION:
Footbridge
END DESCRIPTION:
XS GIS Cut Line= 5
     3199645.031    13825126.102     3200460.806    13825157.068
     3200656.889     13825162.29     3201651.788    13825192.797
     3201767.361     13825195.56
#Sta/Elev= 30
 3945.69   23.85 3993.62   23.84 4032.91   26.41 4093.03   26.71  4126.2   26.63
 4178.03   25.61 4213.04   26.09 4332.72   25.73 4378.56   24.88 4412.91    23.3
  4553.1   26.05 4693.77    26.2 4773.85   24.65    4929   24.53    4938   24.44
    4945   23.59 4957.83   23.29 4987.47   10.44  4995.5   10.36 5001.98   10.49
 5022.17   20.85    5040      22    5129   23.72 5269.88   22.18 5414.35   23.98
 5516.54      22 5711.83   24.21 5825.99   22.96 5872.82    23.7 6069.18   24.25
#Mann= 4 ,-1 , 0
 3945.69     .15       0 4773.85     .07       0 4957.83    .015       0
    5040     .07       0
#XS Ineff= 2 , 0
       0 4957.83   23.29    5040       0      22
Permanent Ineff=
       T       T
#Block Obstruct= 1 ,-1
 3687.71 4537.54   25.04
Bank Sta=4957.83,5040
XS Rating Curve= 0 ,0
Exp/Cntr=0.5,0.3

Type RM Length L Ch R = 3 ,14581   ,,,
BEGIN DESCRIPTION:
Footbridge
END DESCRIPTION:
Bridge Culvert--1,0,-1,-1, 0
Deck Dist Width WeirC Skew NumUp NumDn MinLoCord MaxHiCord MaxSubmerge Is_Ogee
5,12,2.6,0, 3, 3, , , 0.95, 0, 0,0,,
    4956    4968    5022
    23.2   23.75   21.73
   20.62   20.62    18.6
    4956    4968    5022
    23.2   23.75   21.73
   20.62   20.62    18.6
BR Coef=-1 , 1 , 0 ,, 0 ,,,0.8,-1,2,0,
WSPro=,,,, 1 ,,,, 0 ,,,, 0 ,,,,-1 ,-1 ,-1 , 0 , 0 , 0 , 0 , 0
BC Design=,, 0 ,, 0 ,,,,,,
BC HTab HWMax=26.71
BC HTab MaxFlow=2000
BC Use User HTab Curves=0
BC User HTab FreeFlow(D)= 0