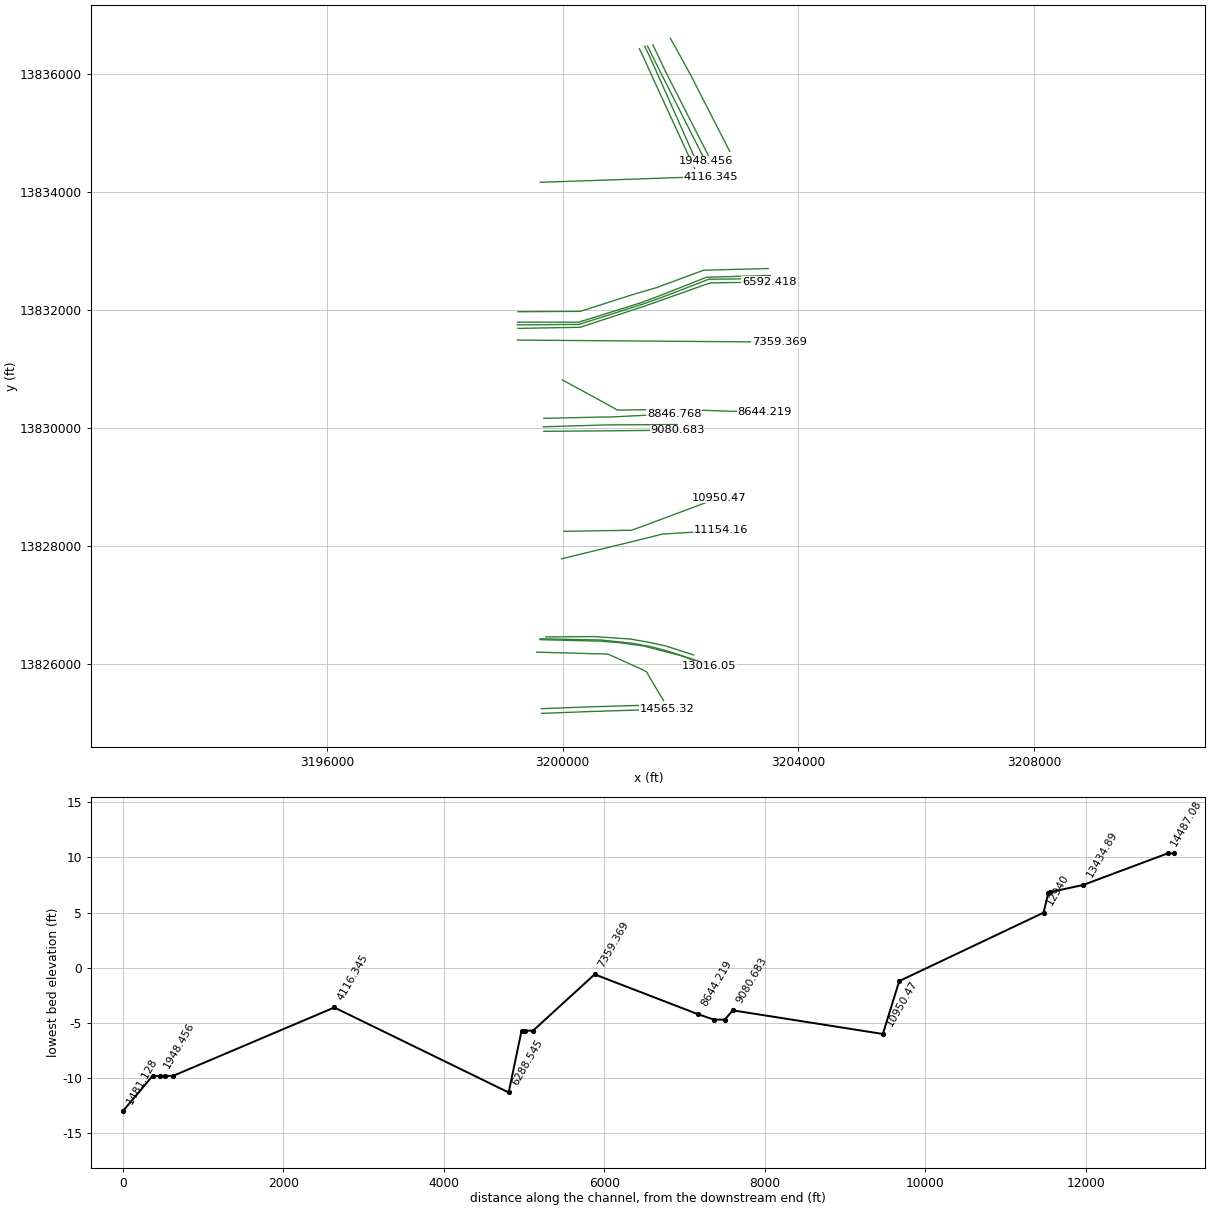
HEC-RAS study G104-00-00.prj: G104-00-00

--- G104-00-00.g01 (geometry) --- (continued)

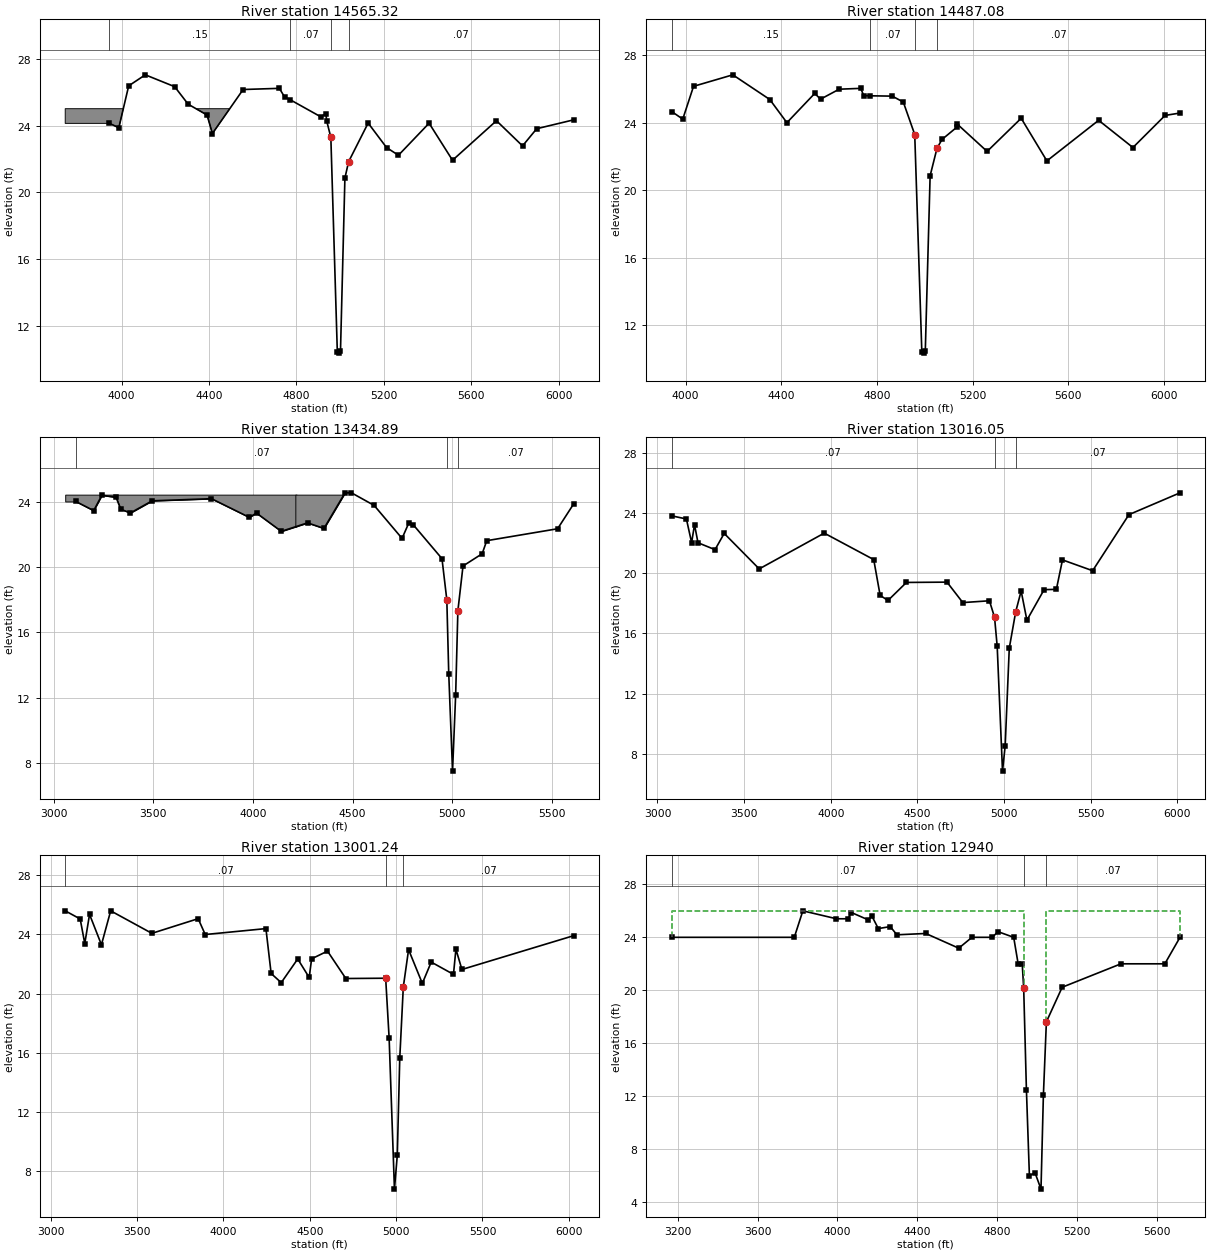
Type RM Length L Ch R = 1 ,14565.32,80.06,78.25,81.51
BEGIN DESCRIPTION:
Footbridge
END DESCRIPTION:
XS GIS Cut Line= 6
     3199643.893    13825156.081     3200459.838    13825187.052
     3200655.284    13825192.258     3200730.372    13825196.251
     3201651.028    13825222.788     3201766.644    13825225.552
#Sta/Elev= 30
  3944.4   24.13 3987.74   23.87 4032.76   26.38  4108.9   27.04 4243.16   26.33
  4304.9   25.28  4391.5   24.63 4415.78   23.52 4556.48   26.16 4722.26   26.23
 4745.84   25.72 4772.74   25.54    4911   24.53    4935    24.7    4939   24.27
 4957.83   23.29 4987.47   10.44  4995.5   10.36 5001.98   10.49 5022.17   20.85
    5039   21.83  5128.5   24.15 5212.78   22.68 5267.18   22.22  5407.4   24.14
 5514.62   21.92 5715.66   24.29    5835   22.78 5899.78   23.81 6068.34   24.34
#Mann= 4 ,-1 , 0
  3944.4     .15       0 4772.74     .07       0 4957.83    .015       0
    5039     .07       0
#XS Ineff= 2 , 0
       0 4957.83   23.29    5039       0   21.83
Permanent Ineff=
       T       T
#Block Obstruct= 1 ,-1
 3742.32 4540.96   25.01
Bank Sta=4957.83,5039
XS Rating Curve= 0 ,0
Exp/Cntr=0.5,0.3

Type RM Length L Ch R = 1 ,14487.08,1245.46,1052.18,551.23
BEGIN DESCRIPTION:
Footbridge
END DESCRIPTION:
XS GIS Cut Line= 6
     3199640.858    13825236.023     3200457.255    13825267.012
     3200651.004    13825272.172     3200731.684    13825273.641
     3201649.002    13825302.762     3201764.732    13825305.529
#Sta/Elev= 30
 3941.73   24.65 3988.09    24.2 4033.12   26.14 4197.37   26.82 4351.92   25.36
 4423.41   23.99 4539.82   25.72 4564.01   25.38 4641.97   25.97 4732.19   26.02
 4744.54   25.59  4770.5   25.58 4863.75   25.56    4910   25.21 4957.83   23.29
 4987.47   10.44  4995.5   10.36 5001.98   10.49 5022.17   20.85    5051   22.48
    5072      23 5133.59   23.72 5133.79   23.93 5260.42   22.29 5402.79   24.25
 5510.31   21.73 5726.62   24.13 5869.98   22.52 6004.58   24.42 6066.77   24.56
#Mann= 4 ,-1 , 0
 3941.73     .15       0  4770.5     .07       0 4957.83    .015       0
    5051     .07       0
Bank Sta=4957.83,5051
XS Rating Curve= 0 ,0
Exp/Cntr=0.3,0.1

Type RM Length L Ch R = 1 ,13434.89,377.52,418.85,509.06
XS GIS Cut Line= 6
      3199560.45    13826194.972     3200768.749    13826161.615
     3201359.744    13825895.029     3201424.211    13825860.729
     3201483.587    13825754.091     3201711.839    13825373.348
#Sta/Elev= 30
 3111.68   24.01 3201.18   23.45 3242.13   24.39 3313.14   24.27 3336.99   23.53
 3385.68   23.31 3494.33   24.05    3792   24.18  3981.4   23.04 4017.79    23.3
 4142.16   22.18 4273.86    22.7  4356.1   22.36 4461.86   24.54 4494.08   24.54
 4607.72   23.77 4747.76   21.75 4781.46   22.69 4804.96   22.57    4948   20.51
 4972.27   17.99 4981.95   13.46 5000.96     7.5 5016.63   12.18 5027.73   17.32
 5053.49   20.06 5149.54   20.81 5172.52   21.61  5527.9   22.34 5607.81   23.85
#Mann= 3 ,-1 , 0
 3111.68     .07       0 4972.27    .015       0 5027.73     .07       0
#Block Obstruct= 2 ,-1
 3058.31 4218.38   24.43 4212.51 4463.94   24.43
Bank Sta=4972.27,5027.73
XS Rating Curve= 0 ,0
Exp/Cntr=0.3,0.1

Type RM Length L Ch R = 1 ,13016.05,16.7,14.81,10.67
BEGIN DESCRIPTION:
Hwy 225
END DESCRIPTION:
XS GIS Cut Line= 6
      3199617.18    13826406.517     3200619.608    13826382.434
     3200977.338    13826353.514     3201369.806    13826299.475
     3201994.062    13826138.719     3202492.311     13825957.52
#Sta/Elev= 30
 3081.81   23.82 3166.84   23.61 3196.84   22.04 3213.61   23.23 3233.72   22.03
 3331.88   21.57 3384.84   22.65 3586.96   20.29 3962.06   22.67 4247.66   20.91
 4284.62   18.53 4329.88   18.19 4436.38   19.39 4670.45   19.41  4761.6   18.05
 4915.25   18.17 4944.67   17.08 4959.99   15.15 4990.71    6.84 5006.08    8.52
 5029.77   15.02 5067.06   17.45 5098.29   18.82 5131.47   16.88 5230.66   18.91
 5301.57   18.93 5336.76   20.89 5510.73   20.17 5720.23    23.9 6014.83   25.35
#Mann= 3 ,-1 , 0
 3081.81     .07       0 4944.67    .015       0 5067.06     .07       0
Bank Sta=4944.67,5067.06
XS Rating Curve= 0 ,0
Exp/Cntr=0.5,0.3

Type RM Length L Ch R = 1 ,13001.24,60,60,60
BEGIN DESCRIPTION:
Hwy 225
END DESCRIPTION:
XS GIS Cut Line= 6
      3199620.19    13826421.568     3200658.741    13826400.496
     3201194.465    13826343.376     3201496.764    13826288.141
     3201780.075    13826213.602     3202508.472    13825975.476
#Sta/Elev= 30
 3083.08   25.59 3169.87   25.04 3196.41   23.38 3224.07   25.35 3292.94    23.3
  3346.5   25.59 3585.18   24.07 3853.19   25.06 3894.16   23.99 4245.78   24.39
 4275.95   21.36 4334.42   20.74 4429.96   22.34 4496.34   21.09 4510.51   22.35
 4602.41   22.87  4708.7   21.02 4939.42   21.04 4959.48      17 4990.24     6.8
  5006.7    9.08 5021.06   15.64  5041.6   20.45 5072.14   22.97 5151.76   20.69
 5203.28   22.13 5332.14    21.3 5346.32      23 5381.04   21.63 6027.66   23.91
#Mann= 3 ,-1 , 0
 3083.08     .07       0 4939.42    .015       0  5041.6     .07       0
Bank Sta=4939.42,5041.6
XS Rating Curve= 0 ,0
Exp/Cntr=0.5,0.3

Type RM Length L Ch R = 1 ,12940   ,1727.71,1798.15,1963.21
BEGIN DESCRIPTION:
Hwy 225.  US face of 2-10X9.  Cross-section added with TSARP 2-ft contours and field survey information in the channel
END DESCRIPTION:
XS GIS Cut Line= 6
    3199713.2727   13826453.8032    3200544.3503    13826458.118
    3201150.0997   13826417.1274     3201482.339   13826357.9188
    3201738.8296   13826302.4258    3202220.8882   13826147.5725
#Sta/Elev= 30
    3170      24 3783.93      24 3826.72      26 3995.13    25.4 4052.18    25.4
 4069.96   25.87 4153.81   25.32 4172.56    25.6 4204.51   24.66 4264.34   24.81
 4297.51   24.19 4442.07   24.29 4607.27   23.18  4673.4      24 4775.99      24
 4803.15   24.43 4882.35      24 4904.62      22 4925.06      22 4932.37   20.17
    4946    12.5    4961       6    4989    6.23    5019    4.99    5031   12.07
    5046   17.62    5125   20.23 5419.39      22    5639      22 5714.95      24
#Mann= 3 , 0 , 0
    3170     .07       0 4932.37    .015       0    5046     .07       0
#XS Ineff= 2 , 0
       0 4932.37      26    5046       0      26
Permanent Ineff=
       T       T
Bank Sta=4932.37,5046
XS Rating Curve= 0 ,0
Exp/Cntr=0.5,0.3

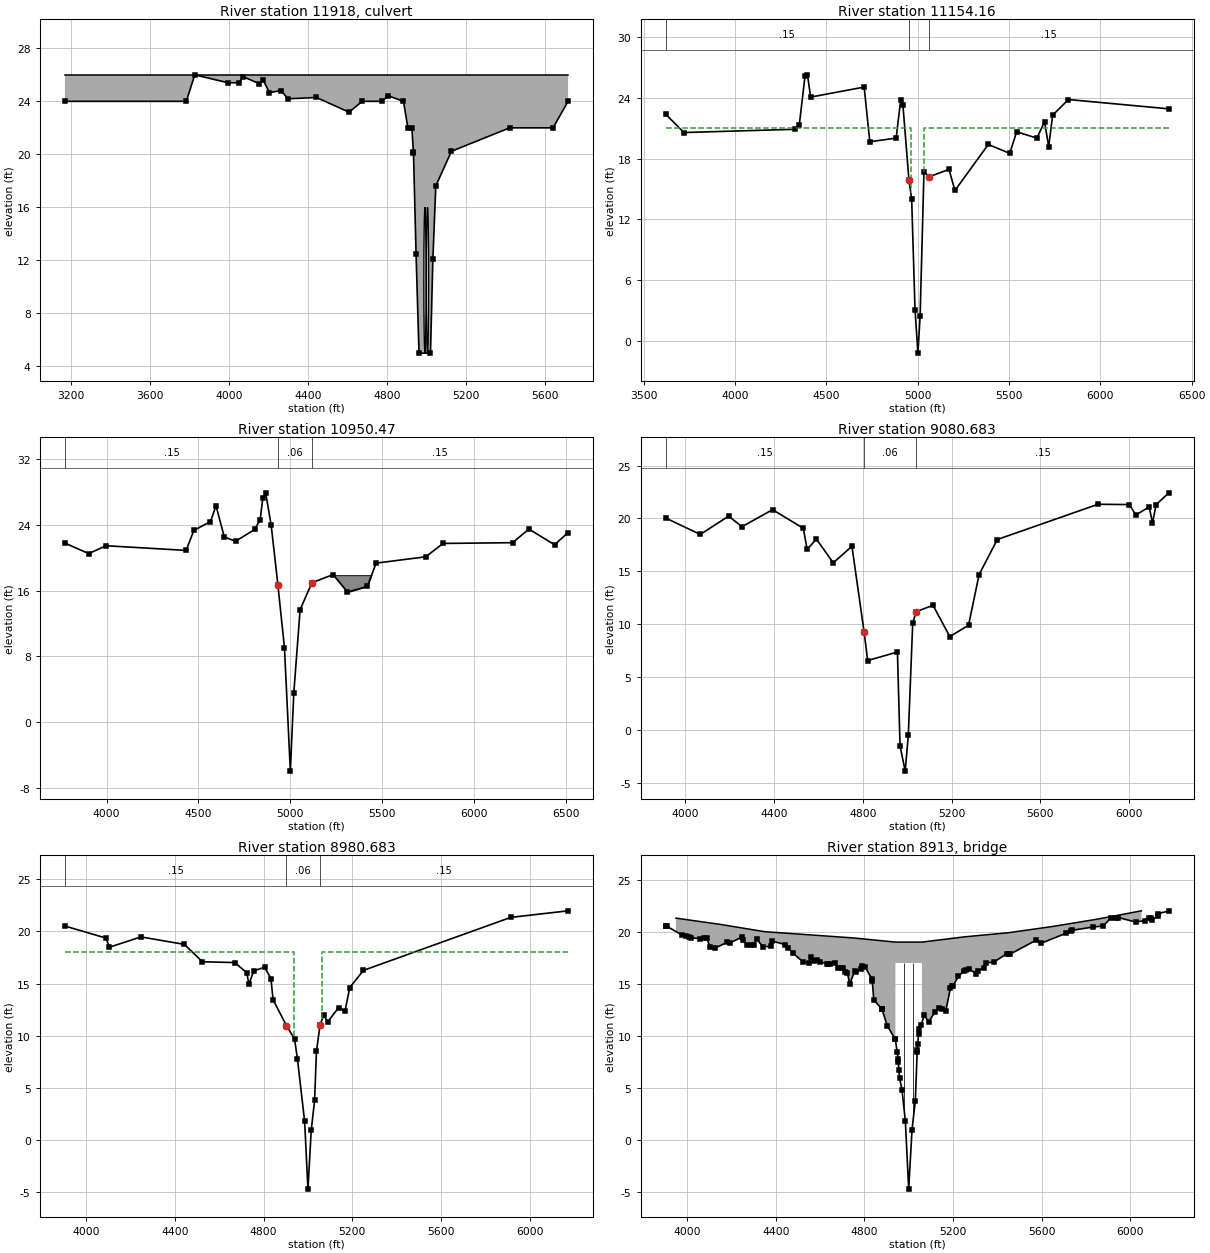
Type RM Length L Ch R = 2 ,11918   ,,,
BEGIN DESCRIPTION:
Long Bridge just north of Hwy 225.  TSARP modified so US face inverts assumed similar to DS invert for the 5-10X9 boxes.
END DESCRIPTION:
Bridge Culvert--1,0,-1,-1, 0
Deck Dist Width WeirC Skew NumUp NumDn MinLoCord MaxHiCord MaxSubmerge Is_Ogee
50,1470,2.6,0, 35, 35, , , 0.95, 0, 0,0,,
    3170    4640    4870  4986.5    4987    4988    4989    4990    4991    4992
    4993    4994    4995    4996    4997    4998    4999    5000    5001    5002
    5003    5004    5005    5006    5007    5008    5009    5010    5011    5012
    5013    5200    5360    5510 5714.95
      26      26      26      26      26      26      26      26      26      26
      26      26      26      26      26      26      26      26      26      26
      26      26      26      26      26      26      26      26      26      26
      26      26      26      26      26
                                                                                
                                                                                
                                                                                
                                        
    3170    4640    4870    4987    4988    4989    4990    4991    4992    4993
    4994    4995    4996    4997    4998    4999    5000    5001    5002    5003
    5004    5005    5006    5007    5008    5009    5010    5011    5012    5013
    5200    5360    5510 5714.95    6374
      26      26      26      26      26      26      26      26      26      26
      26      26      26      26      26      26      26      26      26      26
      26      26      26      26      26      26      26      26      26      26
      26      26      26      26      26
                                                                                
                                                                                
                                                                                
                                        
BR Coef=-1 , 1 , 0 ,, 0 ,,,0.8,0,2,0,
WSPro=,,,, 1 ,,,, 0 ,,,, 0 ,,,,-1 ,-1 ,-1 , 0 , 0 , 0 , 0 , 0
Multiple Barrel Culv=1,11,,1750,0.018,0.5,1,1,1,5,0.2, 2,Culvert #1  , 0 ,10
    4991  4994.5    5004  5007.5
Culvert Bottom n=0.018
BR U #Sta/Elev= 30
    3170      24 3783.93      24 3826.72      26 3995.13    25.4 4052.18    25.4
 4069.96   25.87 4153.81   25.32 4172.56    25.6 4204.51   24.66 4264.34   24.81
 4297.51   24.19 4442.07   24.29 4607.27   23.18  4673.4      24 4775.99      24
 4803.15   24.43 4882.35      24 4904.62      22 4925.06      22 4932.37   20.17
    4933   20.12    4946    12.5    4961       5    5019       5    5031   12.07
    5046   17.62    5125   20.23 5419.39      22    5639      22 5714.95      24
BR U #Mann= 3
    3170     .07 4932.37    .015    5125     .07
BR D #Sta/Elev= 88
 3619.64   22.39 3635.04   22.38 3649.28   22.33 3650.98   22.37 3656.54   22.38
 3658.12   22.35 3719.52   20.58  3878.5   20.62 4031.06   20.52 4325.76    20.9
  4351.5   21.37 4361.08   22.95 4382.38   26.12 4396.16   26.28 4397.82   26.29
  4409.9    24.5 4413.24   24.08 4424.92   24.05 4474.94   23.93 4521.86   23.95
 4547.42   23.92  4663.3   23.77 4705.64   25.02 4706.58   25.07 4707.08   25.03
 4713.28   24.43    4722   23.63 4736.06   20.05 4737.44   19.67 4755.38   19.69
  4856.3   19.56 4876.38   19.94 4880.16   20.01  4881.7   20.03 4903.36   23.33
  4906.5   23.81 4907.28   23.78  4918.9   23.27 4930.78   20.83 4951.84   15.85
 4953.62   15.34    4962    15.1  4966.6   14.04    4985      .2    5001      .2
    5013      .2    5034    16.7 5064.02  16.219 5074.58   16.05 5090.78    16.2
 5145.62   16.68 5166.64    16.9 5171.08   16.94 5186.78   15.78  5200.9   15.03
 5203.72   14.86  5220.6   15.16 5250.56   15.98 5287.88   17.73 5292.36   17.87
 5304.32   17.68  5365.5   18.25 5380.46   19.06 5386.36    19.4 5406.48    19.2
 5473.06   18.48  5503.6   18.52 5517.68   19.08 5541.54   20.65 5584.34   20.49
 5652.32   20.03  5678.6   21.51 5694.36   21.65 5715.84   19.36 5716.98   19.18
  5718.3   19.34 5719.78    19.5 5738.74   22.29 5792.66    23.3 5811.58   23.77
 5819.36   23.73 5825.06   23.84 5953.12   24.25  6029.8      24    6156   23.62
    6245   22.76 6297.02   21.74 6374.84   22.92
BR D #Mann= 3
 3619.64     .15 4951.84     .06 5064.02     .15
BC Design=,, 0 ,, 0 ,,,,,,
BC HTab HWMax=29
BC HTab MaxFlow=4000
BC Use User HTab Curves=0
BC User HTab FreeFlow(D)= 0

Type RM Length L Ch R = 1 ,11154.16,333.69,203.69,305.78
BEGIN DESCRIPTION:
TSARP channel geometry modified with field survey
END DESCRIPTION:
XS GIS Cut Line= 5
     3199981.095    13827777.951     3201205.849    13828076.057
     3201410.387    13828126.294     3201691.307    13828197.042
     3202683.793    13828258.431
#Sta/Elev= 30
 3619.64   22.39 3719.52   20.58 4325.76    20.9  4351.5   21.37 4382.38   26.12
 4396.16   26.28 4413.24   24.08 4706.58   25.07 4737.44   19.67  4881.7   20.03
  4906.5   23.81  4918.9   23.27 4951.84   15.85  4966.6   14.04    4985    3.09
    5001   -1.21    5013     2.5    5034    16.7 5064.02  16.219 5171.08   16.94
 5203.72   14.86 5386.36    19.4  5503.6   18.52 5541.54   20.65 5652.32   20.03
 5694.36   21.65 5716.98   19.18 5738.74   22.29 5825.06   23.84 6374.84   22.92
#Mann= 3 , 0 , 0
 3619.64     .15       0 4951.84     .06       0 5064.02     .15       0
#XS Ineff= 2 , 0
       0    4962      21    5034       0      21
Permanent Ineff=
       T       T
Bank Sta=4951.84,5064.02
XS Rating Curve= 0 ,0
Exp/Cntr=0.5,0.3

Type RM Length L Ch R = 1 ,10950.47,1761.78,1869.79,1446.77
XS GIS Cut Line= 4
       3200020.4    13828244.495     3201168.305    13828262.633
     3201333.422    13828321.603     3202658.053     13828816.13
#Sta/Elev= 30
 3773.68    21.8 3903.16   20.52 3996.92   21.48 4432.78   20.91 4475.56   23.37
 4565.58   24.42 4595.58   26.36 4640.58   22.55  4701.8   22.02  4805.6   23.46
  4835.6   24.66  4850.6   27.34  4865.6   27.93 4895.62   24.01 4932.14   16.72
 4968.04    9.03    5000      -6 5018.82    3.54 5053.06   13.68 5117.38   16.97
 5232.64   17.96  5310.9   15.83 5418.18   16.52 5467.14   19.36 5736.58   20.13
 5831.04   21.76 6209.16   21.85 6297.88   23.51  6437.5    21.6    6511   23.08
#Mann= 3 ,-1 , 0
 3773.68     .15       0 4932.14     .06       0 5117.38     .15       0
#Block Obstruct= 1 ,-1
  5232.9 5468.98   17.89
Bank Sta=4932.14,5117.38
XS Rating Curve= 0 ,0
Exp/Cntr=0.3,0.1

Type RM Length L Ch R = 1 ,9080.683,87.82,100,96.49
BEGIN DESCRIPTION:
Railroad Bridge Channel geometry modified with field survey
END DESCRIPTION:
XS GIS Cut Line= 4
     3199681.413    13829940.607     3200721.377    13829948.834
     3200824.048    13829949.915     3201950.753    13829959.758
#Sta/Elev= 30
 3910.68   20.04  4066.7   18.49 4194.58   20.22 4254.82   19.22 4392.78   20.83
 4531.46   19.07 4548.76   17.08 4590.56   18.05 4666.48   15.81 4750.82   17.37
 4805.92    9.24 4821.78    6.58    4956    7.39  4967.8   -1.47    4991   -3.86
    5005    -.49    5025   10.15 5040.84    11.2 5116.48    11.8  5192.2    8.85
 5276.76    9.91 5324.34    14.7 5406.38   18.01 5860.78   21.34 6002.32   21.31
 6031.52   20.33 6091.52   21.09 6106.52   19.58 6122.86    21.3  6180.1   22.42
#Mann= 3 ,-1 , 0
 3910.68     .15       0 4805.92     .06       0 5040.84     .15       0
Bank Sta=4805.92,5040.84
XS Rating Curve= 0 ,0
Exp/Cntr=0.5,0.3

Type RM Length L Ch R = 1 ,8980.683,143.91,133.91,186.6
BEGIN DESCRIPTION:
Railroad Bridge
END DESCRIPTION:
XS GIS Cut Line= 4
     3199671.838    13830017.209     3200720.851    13830048.834
     3200822.303    13830049.902     3201941.177     13830055.51
#Sta/Elev= 30
 3903.67   20.52 4088.51   19.37 4104.53   18.49 4246.47   19.48 4442.84   18.76
  4523.6    17.1 4669.37   17.02 4723.74   16.06 4733.77   14.94  4755.7   16.23
 4804.43   16.57 4833.06   15.49 4842.49   13.46 4903.07   10.98 4939.49    9.69
 4952.28    7.82    4985     1.8    5000    -4.7    5015       1    5030     3.8
 5038.23     8.5 5054.62   11.04 5071.11   11.97  5089.5   11.34 5138.26   12.71
 5166.92   12.35 5188.53   14.62 5250.21   16.27 5914.75   21.35 6173.51   21.98
#Mann= 3 ,-1 , 0
 3903.67     .15       0 4903.07     .06       0 5054.62     .15       0
#XS Ineff= 2 , 0
       0    4936      18    5064       0      18
Permanent Ineff=
       T       T
Bank Sta=4903.07,5054.62
XS Rating Curve= 0 ,0
Exp/Cntr=0.5,0.3

Type RM Length L Ch R = 3 ,8913    ,,,
BEGIN DESCRIPTION:
Railroad Bridge
END DESCRIPTION:
Bridge Culvert--1,0,-1,-1, 0
Deck Dist Width WeirC Skew NumUp NumDn MinLoCord MaxHiCord MaxSubmerge Is_Ogee
4,120,2.6,0, 15, 15, , , 0.95, 0, 0,0,,
    3950    4150    4350    4550    4750    4940    4940    5000    5060    5060
    5250    5450    5650    5850    6050
    21.3    20.7      20    19.7    19.4      19      19      19      19      19
    19.5    19.9    20.5    21.2      22
       0       0       0       0       0       0      17      17      17       0
       0       0       0       0       0
    3950    4150    4350    4550    4750    4940    4940    5000    5060    5060
    5250    5450    5650    5850    6050
    21.3    20.7      20    19.7    19.4      19      19      19      19      19
    19.5    19.9    20.5    21.2      22
       0       0       0       0       0       0      17      17      17       0
       0       0       0       0       0
Pier Skew, UpSta & Num, DnSta & Num=  ,4980, 2 ,4980, 2 , 0 , 0 , 0 ,,
     1.9     1.9
      -5      18
     1.9     1.9
      -5      18
Pier Skew, UpSta & Num, DnSta & Num=  ,5020, 2 ,5020, 2 , 0 , 0 , 0 ,,
     1.9     1.9
      -5      18
     1.9     1.9
      -5      18
Abutment Skew #Up #Dn= , 2 , 2
    4940    4975
      18    3.75
    4940    4975
      18    3.75
Abutment Skew #Up #Dn= , 2 , 2
    5025    5060
    2.85      18
    5025    5060
    2.85      18
BR Coef=-1 , 1 , 0 ,, 0 ,,,0.8,-1,2,0,
WSPro=,,,, 1 ,,,, 0 ,,,, 0 ,,,,-1 ,-1 ,-1 , 0 , 0 , 0 , 0 , 0
BR U #Sta/Elev= 113
 3903.67   20.52 3903.71   20.52 3905.12   20.52 3907.71   20.53 3979.05   19.66
 3997.51   19.58 4009.07   19.47 4019.95   19.41  4059.4   19.33 4078.22   19.41
 4088.51   19.37 4104.53   18.49 4127.06   18.43 4180.15   18.97 4195.51   18.93
 4246.47   19.48 4253.03   19.16 4270.01   18.71 4288.09   18.69 4300.49   18.75
 4313.46   19.32 4341.59   18.56 4376.67   18.58 4384.24    19.1 4442.84   18.76
 4456.73   18.44 4477.42   17.94  4523.6    17.1 4549.31   16.97 4559.51   17.59
 4573.52   17.19 4585.49   17.28 4598.56   17.09 4631.91   16.93 4635.69   16.88
 4646.36   16.93 4669.37   17.02 4681.28   16.52 4699.38   16.56 4704.63   16.51
 4714.39   16.17 4723.74   16.06 4733.77   14.94  4755.7   16.23  4762.9   16.16
 4786.64   16.43 4790.75   16.68 4804.43   16.57 4833.06   15.49 4835.74   15.23
 4842.49   13.46 4879.41   12.56 4879.45   12.56 4879.47   12.56 4879.53   12.56
 4903.07   10.98 4937.71    9.74 4939.49    9.69 4947.79    8.48 4952.28    7.82
 4953.16    7.53 4955.63    6.71 4959.14    5.95    4970     4.8    4985     1.8
    5000    -4.7    5015       1    5030     3.8 5038.23     8.5 5038.59     8.6
 5040.86    9.19  5044.5   10.15 5047.74   10.65 5054.62   11.04 5071.11   11.97
  5089.5   11.34 5117.44   12.25 5138.26   12.71 5151.31   12.58 5166.92   12.35
 5188.53   14.62  5194.5   14.77 5198.53   14.78  5224.5    15.7 5250.21   16.27
 5257.39   16.33  5272.1   16.42 5304.06   15.98  5314.5   16.24 5337.66   16.54
 5349.61   17.03 5382.83   17.06  5442.5   17.89 5451.27   17.83 5455.89   17.83
 5574.05   19.17 5598.53    18.9 5708.17   19.83 5732.28   20.06    5739   20.14
 5830.66   20.44 5876.99   20.55 5914.75   21.35 5934.71   21.35 5946.36   21.35
 6024.97   20.92 6065.21   21.07 6085.82    21.3 6094.51   21.28 6096.13    21.1
 6122.93   21.49 6125.78   21.74 6173.51   21.98
BR U #Mann= 3
 3903.67     .15 4903.07     .04 5054.62     .15
BC Design=,, 0 ,, 0 ,,,,,,
BC HTab HWMax=10
BC HTab MaxFlow=4000
BC Use User HTab Curves=0
BC User HTab FreeFlow(D)= 0

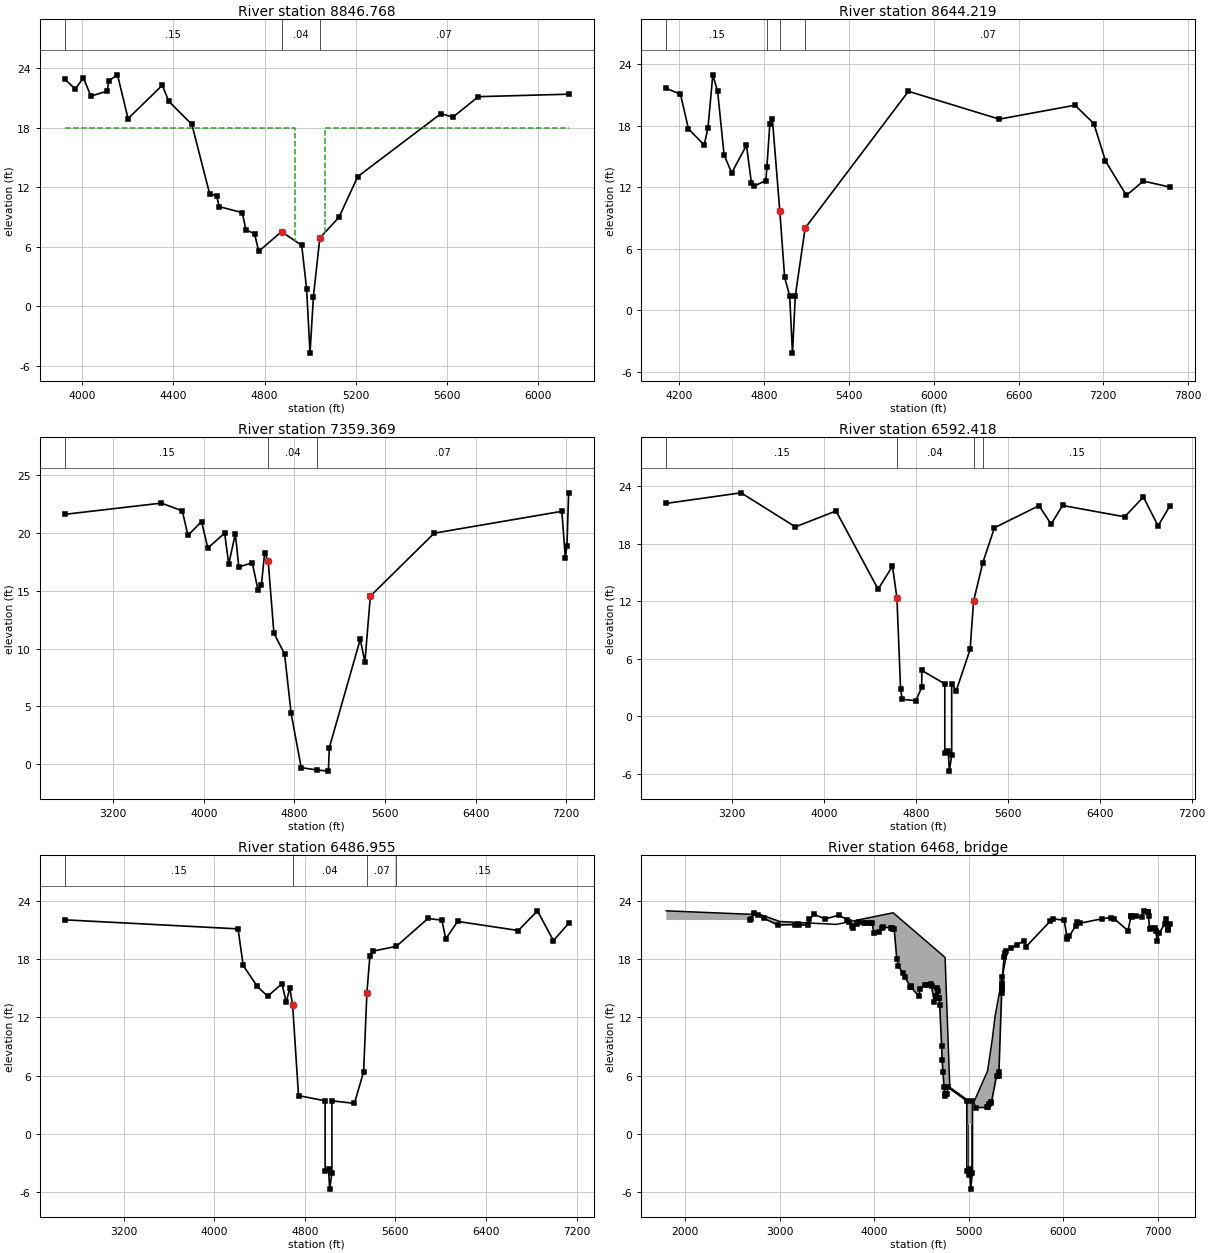
Type RM Length L Ch R = 1 ,8846.768,589.22,202.55,83.12
BEGIN DESCRIPTION:
Railroad Bridge
END DESCRIPTION:
XS GIS Cut Line= 5
     3199681.413    13830160.838     3200663.717    13830182.857
       3200734.2    13830182.857      3200813.76    13830183.391
     3201893.301    13830237.441
#Sta/Elev= 30
 3923.14   22.87  3968.4   21.91 4003.92   23.02 4037.14   21.19 4108.96   21.69
 4115.74   22.72 4153.96   23.33 4200.36   18.92 4350.94   22.28 4379.02   20.67
 4480.68   18.34 4559.06   11.33 4589.08   11.16  4601.3   10.05 4702.42    9.45
 4718.12    7.72  4756.2    7.33 4774.68    5.55 4874.94    7.54 4963.48    6.15
    4985     1.8    5000    -4.7    5015       1 5043.16     6.9 5127.26    8.98
 5209.84   13.08 5575.38   19.42 5628.04   19.07 5739.68   21.13 6136.62   21.38
#Mann= 3 ,-1 , 0
 3923.14     .15       0 4874.94     .04       0 5043.16     .07       0
#XS Ineff= 2 , 0
       0    4936      18    5064       0      18
Permanent Ineff=
       T       T
Bank Sta=4874.94,5043.16
XS Rating Curve= 0 ,0
Exp/Cntr=0.5,0.3

Type RM Length L Ch R = 1 ,8644.219,769.98,1284.85,1315.8
BEGIN DESCRIPTION:
Railroad Bridge
END DESCRIPTION:
XS GIS Cut Line= 6
      3199997.39    13830811.957      3200667.46    13830447.364
     3200930.312    13830300.721     3201902.876    13830314.043
     3202918.647    13830278.713     3203430.779    13830273.594
#Sta/Elev= 30
 4106.96   21.66 4207.12    21.1 4263.66   17.71 4374.82   16.13 4401.74    17.8
  4435.9   22.99 4470.04   21.37 4515.78   15.17 4569.66   13.41 4674.38   16.11
 4709.12   12.43 4727.96   12.12 4811.58   12.66 4818.76   13.94  4839.7   18.22
 4857.56   18.67  4910.4    9.64 4944.44     3.2    4980     1.4    5000    -4.2
    5020     1.4  5089.6    8.02  5820.5   21.38 6463.53   18.66 6999.21   20.02
 7132.98   18.23 7215.48   14.57 7363.37   11.21 7483.38   12.61 7671.98   12.02
#Mann= 4 ,-1 , 0
 4106.96     .15       0 4818.76     .07       0  4910.4     .04       0
  5089.6     .07       0
Bank Sta=4910.4,5089.6
XS Rating Curve= 0 ,0
Exp/Cntr=0.3,0.1

Type RM Length L Ch R = 1 ,7359.369,231.16,766.95,1088.52
XS GIS Cut Line= 2
      3199231.79    13831488.434     3203677.258    13831454.369
#Sta/Elev= 30
 2774.98   21.62 3625.56   22.59 3810.25   21.92 3860.41    19.8 3980.38   20.99
 4035.85    18.7 4184.38   19.99 4220.42   17.31 4278.65   19.94 4309.41   17.06
 4428.21   17.43 4479.21   15.05 4508.98   15.52 4537.65   18.31 4568.53   17.56
 4619.29   11.33 4713.23    9.54 4770.95    4.41    4860     -.3    5000     -.5
    5100     -.6 5108.24    1.43 5381.39   10.81 5422.18    8.83 5470.37   14.54
  6034.1   19.99 7160.51   21.88 7191.17   17.88 7205.51   18.87 7220.58   23.48
#Mann= 3 ,-1 , 0
 2774.98     .15       0 4568.53     .04       0    5000     .07       0
Bank Sta=4568.53,5470.37
XS Rating Curve= 0 ,0
Exp/Cntr=0.3,0.1

Type RM Length L Ch R = 1 ,6592.418,55,105.46,63.15
BEGIN DESCRIPTION:
Footbridge
END DESCRIPTION:
XS GIS Cut Line= 6
     3199242.024    13831686.963     3200297.254    13831705.096
     3201399.702     13832067.84     3201787.282     13832204.73
     3202501.959    13832458.048     3203502.079    13832473.318
#Sta/Elev= 30
 2625.25   22.22 3276.03   23.32 3748.99   19.77 4103.05   21.43  4469.3   13.27
 4594.38   15.67  4633.3   12.35 4664.88    2.89 4678.66    1.79 4798.18    1.65
  4848.7    3.03    4850     4.8    5050     3.4    5050    -3.8    5080    -3.6
    5090    -5.7    5110      -4    5110     3.4    5150     2.7 5270.42    6.99
 5300.41   12.03  5381.4   16.05 5482.34   19.68 5870.28   21.98 5975.68   20.06
 6075.75      22 6615.81   20.82 6779.13   22.88 6907.13   19.87 7010.75   21.98
#Mann= 4 ,-1 , 0
 2625.25     .15       0  4633.3     .04       0 5300.41     .07       0
  5381.4     .15       0
Bank Sta=4633.3,5300.41
XS Rating Curve= 0 ,0
Exp/Cntr=0.5,0.3

Type RM Length L Ch R = 1 ,6486.955,38.75,37.87,37.25
BEGIN DESCRIPTION:
Footbridge
END DESCRIPTION:
XS GIS Cut Line= 6
     3199231.082    13831746.118     3200277.997     13831754.18
     3201363.782    13832099.547     3201671.535    13832208.719
     3202480.849    13832520.562     3203547.694    13832532.615
#Sta/Elev= 30
 2683.06   22.05  4211.2   21.12 4256.84   17.35 4381.28   15.19 4472.22   14.17
 4599.06   15.47 4636.08   13.58 4668.34   15.02    4693   13.27 4745.18    3.94
    4980     3.4    4980    -3.8    5010    -3.6    5020    -5.7    5040      -4
    5040     3.4 5238.62    3.14 5319.88    6.39 5348.98   14.56 5375.12   18.28
 5398.62   18.82 5609.08   19.32 5887.62   22.19  6011.1   22.02  6045.1   20.09
  6149.6   21.89  6685.8   20.95 6854.64   22.98 6995.78   19.91 7130.16   21.69
#Mann= 4 ,-1 , 0
 2683.06     .15       0    4693     .04       0 5348.98     .07       0
 5609.08     .15       0
#XS Ineff= 2 , 0
       0    4975     3.4    5045       0     3.2
Permanent Ineff=
       T       T
Bank Sta=4693,5348.98
XS Rating Curve= 0 ,0
Exp/Cntr=0.5,0.3

Type RM Length L Ch R = 3 ,6468    ,,,
BEGIN DESCRIPTION:
Footbridge
END DESCRIPTION:
Bridge Culvert--1,0,-1,-1, 0
Deck Dist Width WeirC Skew NumUp NumDn MinLoCord MaxHiCord MaxSubmerge Is_Ogee
5,23,2.6,0, 13, 13, , , 0.95, 0, 0,0,,
    1800    2800    3000    3600    4200    4750    4800    5000    5060    5200
    5250    5280    5400
      23    22.6    21.9    21.6    22.8    18.2     4.8     3.4     3.4     6.5
     9.8    12.2    18.5
       1       1       1       1       1       1       1       1       1       1
       1       1       1
    1900    2900    3100    3700    4300    4850    4900    5100    5160    5300
    5350    5380    5500
      23    22.6    21.9    21.6    22.8    18.2     4.8     3.4     3.4     6.5
     9.8    12.2    18.5
       1       1       1       1       1       1       1       1       1       1
       1       1       1
Pier Skew, UpSta & Num, DnSta & Num=  ,4995, 2 ,5095, 2 , 0 , 0 , 0 ,,
    1.63    1.63
     -10       2
    1.63    1.63
     -10       2
Pier Skew, UpSta & Num, DnSta & Num=  ,5025, 2 ,5125, 2 , 0 , 0 , 0 ,,
    1.63    1.63
     -10       2
    1.63    1.63
     -10       2
BR Coef=-1 , 1 , 0 ,, 0 ,,,0.8,0,2,0,
WSPro=,,,, 1 ,,,, 0 ,,,, 0 ,,,,-1 ,-1 ,-1 , 0 , 0 , 0 , 0 , 0
BR U #Sta/Elev= 124
 2683.06   22.05 2693.76   22.11 2728.42   22.76 2766.56   22.62  2830.8   22.23
 2978.32   21.54 3164.96   21.58 3192.62   21.69    3207   21.55 3304.18   21.53
 3313.08   22.11 3362.44   22.63 3483.96   22.16 3622.22   22.55 3717.04   22.09
    3730   21.85 3760.26   21.47 3775.06   21.26 3818.34   21.66 3836.94   21.84
 3890.26   21.79 3918.36   21.73    3957   21.76 3975.76   21.77 3997.44   20.72
 4054.32   20.85 4085.94   21.23 4095.98    21.3  4178.2   21.26 4184.74   21.19
 4197.32   21.14  4211.2   21.12 4238.72   18.07 4256.84   17.35  4300.8   16.55
 4325.84   16.14 4381.28   15.19    4385   15.21 4387.46   15.17 4472.22   14.17
 4487.94   14.98 4532.42    15.4  4573.9   15.31 4599.06   15.47 4607.64    15.2
 4636.08   13.58  4651.1   14.22 4668.34   15.02 4670.72   14.76 4684.08   13.99
 4684.26   13.97    4693   13.27 4713.26     9.1 4718.48    7.64 4727.68     6.4
 4739.52    4.79 4745.18    3.94  4750.7    4.07 4762.78     4.1 4769.42    4.12
    4780     4.8    4980     3.4    4980    -3.8    5000    -4.2    5010    -3.6
    5020    -5.7    5040      -4    5040     3.4    5080     2.7 5195.94    2.73
    5201    2.77 5211.48     3.1 5237.34    3.32 5238.62    3.14 5294.98    6.01
  5315.8    5.97 5319.88    6.39 5348.98   14.56 5350.86   14.94 5351.32   15.09
 5352.02   15.31 5353.38   15.53  5356.9   16.22 5375.12   18.28  5388.2   18.62
 5398.62   18.82 5450.58   19.18 5510.92   19.48 5584.22   19.92 5609.08   19.32
 5864.82   21.96 5887.62   22.19  6011.1   22.02 6038.82   20.33  6045.1   20.09
 6063.24   20.37 6131.48   21.44  6149.6   21.89 6175.18   21.72 6412.64   22.18
 6507.52   22.31 6540.46   22.18  6685.8   20.95 6717.08   22.42  6720.9   22.48
 6729.38   22.41 6765.38   22.43 6832.06   22.36 6854.64   22.98 6894.66   22.91
 6897.44   22.91 6902.92   22.44 6914.64    21.1  6924.1   21.21 6971.76   21.24
  6977.5   20.97 6995.78   19.91  7016.4   20.71 7073.88   21.64  7092.3   22.16
 7106.06   21.11 7109.66   21.01  7112.9   21.14 7130.16   21.69
BR U #Mann= 4
 2683.06     .15    4693     .03 5348.98     .07 5609.08     .15
BC Design=,, 0 ,, 0 ,,,,,,
BC HTab HWMax=8
BC HTab MaxFlow=7000
BC Use User HTab Curves=0
BC User HTab FreeFlow(D)= 0

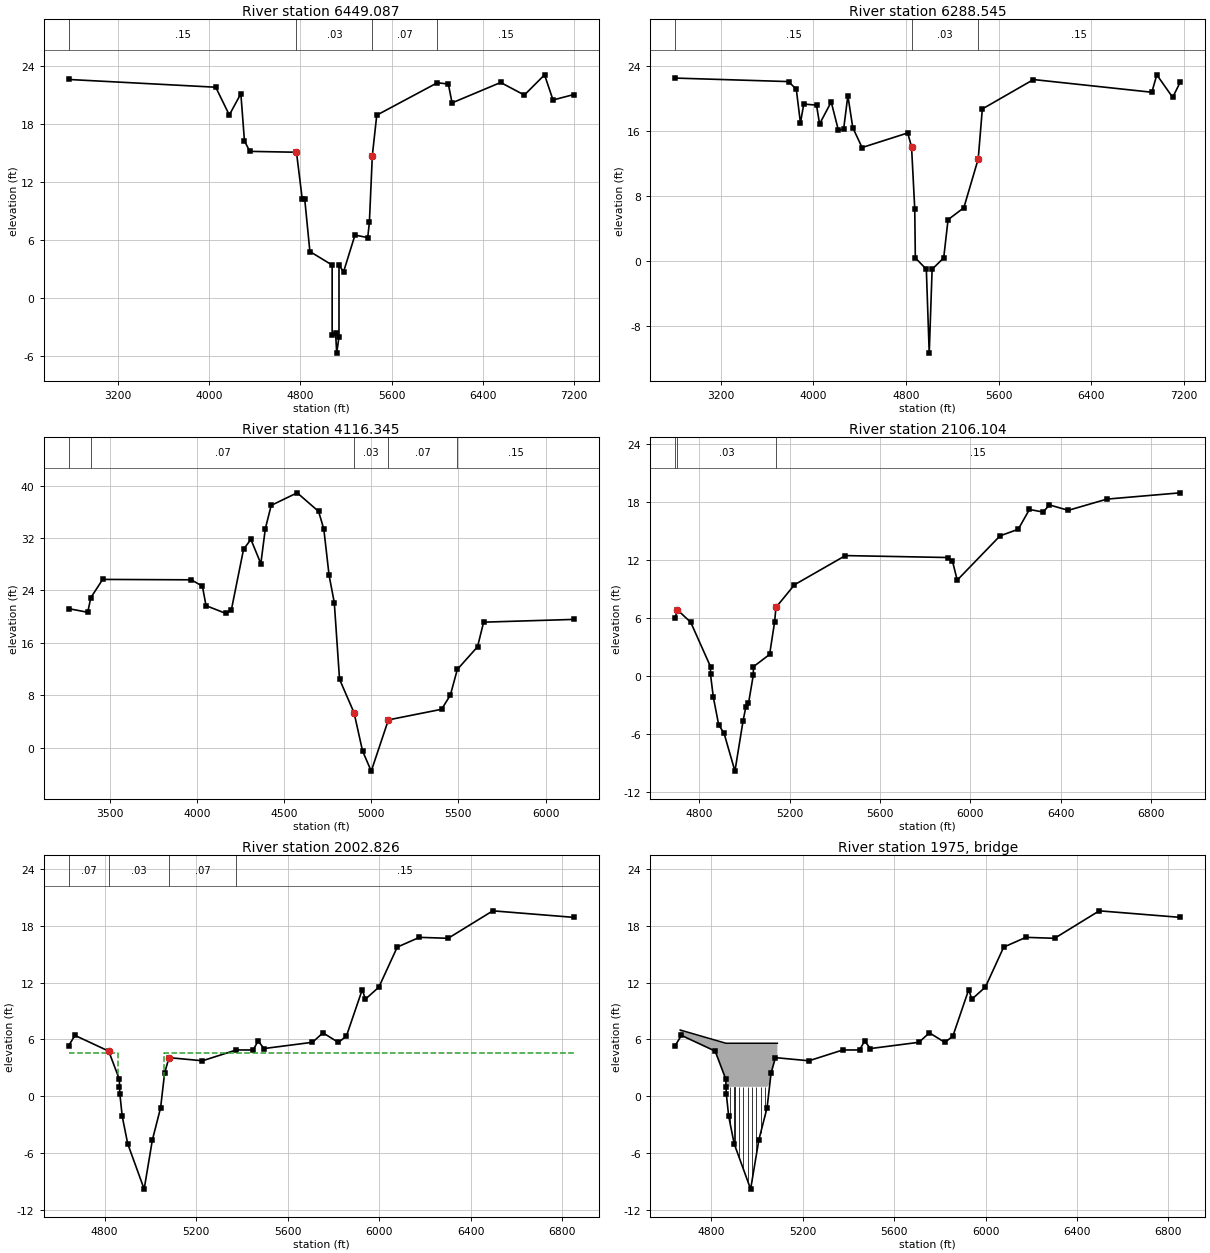
Type RM Length L Ch R = 1 ,6449.087,175.54,160.54,120.99
BEGIN DESCRIPTION:
Footbridge
END DESCRIPTION:
XS GIS Cut Line= 6
     3199236.151    13831792.096     3200274.707    13831792.096
      3201328.96    13832122.134     3201632.948    13832235.071
     3202442.132    13832555.007     3203527.496    13832584.043
#Sta/Elev= 30
  2772.8   22.58  4060.2   21.78 4179.09   18.91 4280.25   21.11 4311.69   16.24
 4358.25   15.15  4767.5   15.06 4817.74   10.25 4839.46   10.25    4885     4.8
    5080     3.4    5080    -3.8    5110    -3.6    5120    -5.7    5140      -4
    5140     3.4    5180     2.7    5280     6.5 5391.66    6.24 5406.21     7.8
 5432.07   14.72 5470.73   18.89 6001.68   22.24 6097.94   22.11 6130.55   20.16
  6556.4   22.27  6763.8   20.97 6940.84   23.06 7015.07   20.46 7196.24   21.02
#Mann= 4 ,-1 , 0
  2772.8     .15       0  4767.5     .03       0 5432.07     .07       0
 6001.68     .15       0
#XS Ineff= 2 , 0
       0    5075     3.4    5145       0     3.2
Permanent Ineff=
       T       T
Bank Sta=4767.5,5432.07
XS Rating Curve= 0 ,0
Exp/Cntr=0.5,0.3

Type RM Length L Ch R = 1 ,6288.545,2215,2172.2,1628.59
XS GIS Cut Line= 6
     3199242.024     13831969.44     3200301.178     13831975.82
     3201202.398    13832264.407     3201588.567     13832376.52
     3202391.572    13832673.648      3203486.81    13832702.353
#Sta/Elev= 30
 2807.22   22.48 3785.64   22.05  3852.4    21.1 3888.14   16.96  3916.6   19.29
 4026.88   19.16  4053.2   16.84  4153.8   19.55 4216.12   16.05  4261.2   16.24
 4297.58   20.33 4339.96   16.39 4420.32   13.95 4814.28   15.74 4847.42   14.03
 4875.02    6.41    4880      .4    4975      -1    5000   -11.3    5025      -1
    5125      .4  5162.5    5.09 5298.64    6.55 5422.86   12.54 5458.56   18.69
 5900.14    22.3 6921.92   20.74 6964.96   22.88 7101.98   20.11 7166.62   21.97
#Mann= 3 ,-1 , 0
 2807.22     .15       0 4847.42     .03       0 5422.86     .15       0
Bank Sta=4847.42,5422.86
XS Rating Curve= 0 ,0
Exp/Cntr=0.3,0.1

Type RM Length L Ch R = 1 ,4116.345,2655.63,2010.24,291.15
XS GIS Cut Line= 3
     3199620.696    13834164.971     3202200.345    13834253.017
     3202514.276    13834251.903
#Sta/Elev= 30
 3265.84   21.22 3374.28   20.67  3392.4   22.91 3459.96   25.69 3967.36   25.63
  4031.8   24.67  4052.8   21.68 4166.98   20.49  4197.8      21  4267.8   30.28
 4309.96   31.81 4367.04    28.1 4392.56   33.41 4426.24      37 4575.42   38.92
 4698.16   36.08 4728.18   33.37  4758.2   26.34 4788.22   22.13 4818.24   10.44
 4901.56    5.31    4950     -.5    5000    -3.6 5098.44    4.23 5403.58    5.85
 5453.84    8.03 5493.64   11.94 5609.54    15.4 5644.34   19.16 6160.92   19.58
#Mann= 5 ,-1 , 0
 3265.84     .15       0  3392.4     .07       0 4901.56     .03       0
 5098.44     .07       0 5493.64     .15       0
Bank Sta=4901.56,5098.44
XS Rating Curve= 0 ,0
Exp/Cntr=0.3,0.1

Type RM Length L Ch R = 1 ,2106.104,101.06,103.28,117.33
BEGIN DESCRIPTION:
Bridge near mouth
END DESCRIPTION:
XS GIS Cut Line= 4
     3201301.594    13836430.556     3201384.397    13836259.043
     3201533.805    13835926.272     3202236.567    13834401.157
#Sta/Elev= 30
 4693.88    6.02 4702.36     6.9  4762.4    5.59    4850       1    4850      .2
    4862    -2.1    4886      -5    4910    -5.9    4958    -9.8    4994    -4.6
    5006    -3.2    5018    -2.8    5039      .1    5040       1 5111.47    2.27
 5133.66    5.64 5139.48    7.13 5221.41    9.47 5446.95   12.49 5899.27   12.29
 5920.78    11.9 5941.75    9.95 6131.16   14.53 6211.64   15.21 6261.27   17.26
  6322.1   16.99 6349.64   17.73 6433.17   17.17 6604.04   18.33 6928.35   18.98
#Mann= 3 ,-1 , 0
 4693.88     .07       0 4702.36     .03       0 5139.48     .15       0
Bank Sta=4702.36,5139.48
XS Rating Curve= 0 ,0
Exp/Cntr=0.5,0.3

Type RM Length L Ch R = 1 ,2002.826,45.96,54.37,185.6
BEGIN DESCRIPTION:
Bridge near mouth
END DESCRIPTION:
XS GIS Cut Line= 4
     3201391.648    13836474.033     3201475.055    13836301.269
     3201625.075    13835967.134     3202295.232    13834459.823
#Sta/Elev= 30
 4643.46    5.36 4670.34    6.43 4817.86    4.77 4864.92    1.78    4865       1
    4867      .2    4877    -2.1    4901      -5    4973    -9.8    5009    -4.6
    5045    -1.2 5062.32    2.44 5081.58    4.08 5228.02    3.75 5375.82    4.89
 5449.32    4.89 5471.54    5.84 5496.84    5.04 5708.88     5.7 5754.82     6.7
 5822.14    5.69 5857.22    6.35 5926.66   11.26 5940.32   10.25 5999.44   11.53
 6079.58   15.75 6176.68   16.78 6302.12   16.68 6497.48   19.58 6851.14   18.89
#Mann= 4 ,-1 , 0
 4643.46     .07       0 4817.86     .03       0 5081.58     .07       0
 5375.82     .15       0
#XS Ineff= 2 , 0
       0    4860     4.6    5060       0     4.6
Permanent Ineff=
       T       T
Bank Sta=4817.86,5081.58
XS Rating Curve= 0 ,0
Exp/Cntr=0.5,0.3

Type RM Length L Ch R = 3 ,1975    ,,,
BEGIN DESCRIPTION:
Bridge near mouth
END DESCRIPTION:
Bridge Culvert--1,0,-1,-1, 0
Deck Dist Width WeirC Skew NumUp NumDn MinLoCord MaxHiCord MaxSubmerge Is_Ogee
18,20,2.6,0, 4, 4, , , 0.95, 0, 0,0,,
    4665    4865    5057    5090
       7     5.6     5.6     5.6
       1       1       1       1
    4715    4915    5107    5140
       7     5.6     5.6     5.6
       1       1       1       1
Pier Skew, UpSta & Num, DnSta & Num=  ,4884, 2 ,4924, 2 , 0 , 0 , 0 ,,
       1       1
     -10       2
       1       1
     -10       2
Pier Skew, UpSta & Num, DnSta & Num=  ,4903, 2 ,4943, 2 , 0 , 0 , 0 ,,
       1       1
     -10       2
       1       1
     -10       2
Pier Skew, UpSta & Num, DnSta & Num=  ,4922, 2 ,4962, 2 , 0 , 0 , 0 ,,
       1       1
     -10       2
       1       1
     -10       2
Pier Skew, UpSta & Num, DnSta & Num=  ,4941, 2 ,4981, 2 , 0 , 0 , 0 ,,
       1       1
     -10       2
       1       1
     -10       2
Pier Skew, UpSta & Num, DnSta & Num=  ,4960, 2 ,5000, 2 , 0 , 0 , 0 ,,
       1       1
     -10       2
       1       1
     -10       2
Pier Skew, UpSta & Num, DnSta & Num=  ,4979, 2 ,5019, 2 , 0 , 0 , 0 ,,
       1       1
     -10       2
       1       1
     -10       2
Pier Skew, UpSta & Num, DnSta & Num=  ,4998, 2 ,5038, 2 , 0 , 0 , 0 ,,
       1       1
     -10       2
       1       1
     -10       2
Pier Skew, UpSta & Num, DnSta & Num=  ,5017, 2 ,5057, 2 , 0 , 0 , 0 ,,
       1       1
     -10       2
       1       1
     -10       2
Pier Skew, UpSta & Num, DnSta & Num=  ,5036, 2 ,5076, 2 , 0 , 0 , 0 ,,
       1       1
     -10       2
       1       1
     -10       2
BR Coef=-1 , 1 , 0 ,, 0 ,,,0.8,-1,2,0,
WSPro=,,,, 1 ,,,, 0 ,,,, 0 ,,,,-1 ,-1 ,-1 , 0 , 0 , 0 , 0 , 0
BC Design=,, 0 ,, 0 ,,,,,,
BC HTab HWMax=5
BC HTab MaxFlow=7000
BC Use User HTab Curves=0
BC User HTab FreeFlow(D)= 0

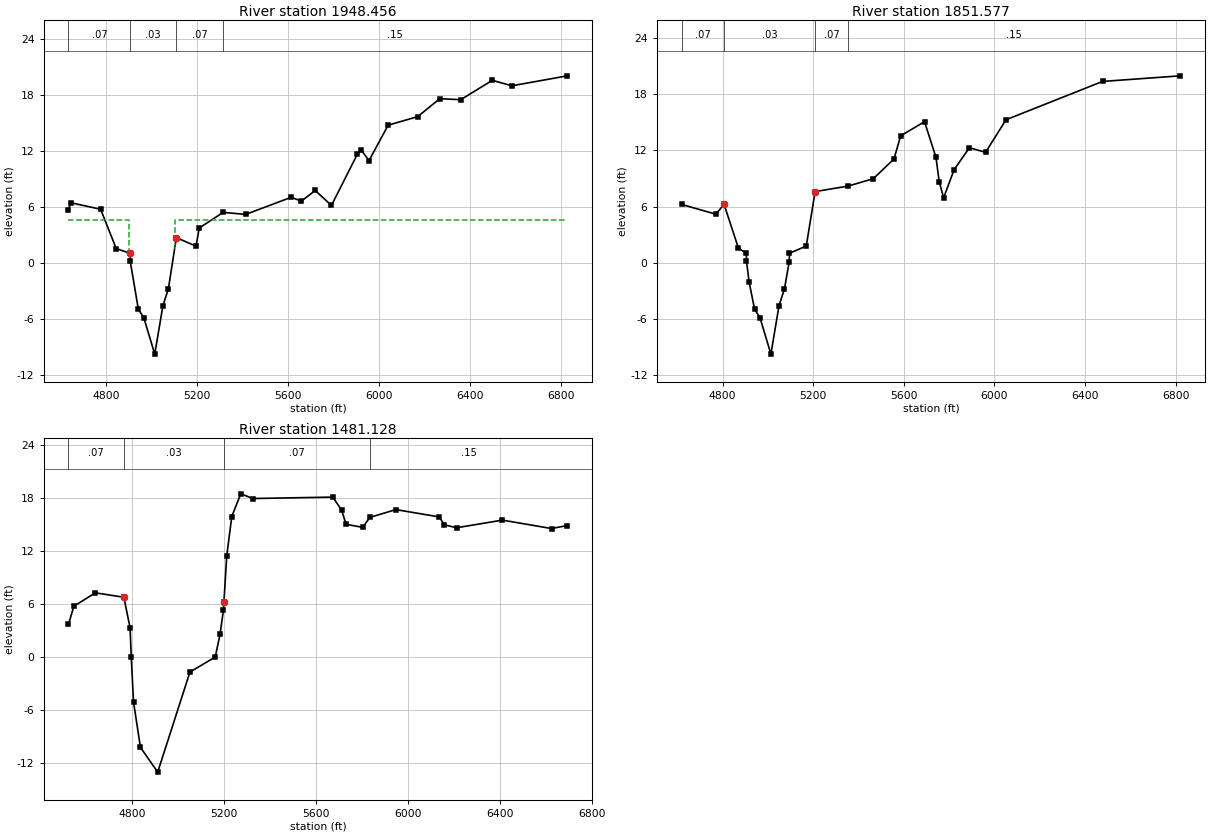
Type RM Length L Ch R = 1 ,1948.456,90.19,96.88,122.43
BEGIN DESCRIPTION:
Bridge near mouth
END DESCRIPTION:
XS GIS Cut Line= 4
     3201440.282    13836478.342     3201515.117    13836321.727
     3201693.266    13835966.282     3202424.296    13834518.488
#Sta/Elev= 30
 4633.76     5.7 4643.19    6.43 4774.99    5.73 4843.64    1.51    4905       1
    4905      .2    4941      -5    4965    -5.9    5013    -9.8    5049    -4.6
    5073    -2.8    5108    2.69 5194.41    1.77 5208.64    3.72 5313.46    5.39
  5413.3    5.18 5612.98    7.01 5657.81     6.6 5718.47    7.74 5789.97    6.14
 5904.01   11.64 5921.54   12.05 5955.14   10.95 6039.16   14.74 6169.42   15.66
  6266.2   17.58 6358.43   17.47 6496.96   19.55 6583.09   18.96 6826.81   20.03
#Mann= 4 ,-1 , 0
 4633.76     .07       0    4905     .03       0    5108     .07       0
 5313.46     .15       0
#XS Ineff= 2 , 0
       0    4900     4.6    5100       0     4.6
Permanent Ineff=
       T       T
Bank Sta=4905,5108
XS Rating Curve= 0 ,0
Exp/Cntr=0.5,0.3

Type RM Length L Ch R = 1 ,1851.577,321.55,370.45,482.83
BEGIN DESCRIPTION:
Bridge near mouth
END DESCRIPTION:
XS GIS Cut Line= 4
     3201529.835    13836497.965     3201670.368    13836204.563
     3201742.713    13836049.286     3202518.161    13834530.221
#Sta/Elev= 30
 4619.02    6.22 4770.24    5.18  4806.2    6.24 4869.86    1.53    4905       1
    4905      .2    4917    -2.1    4941      -5    4965    -5.9    5013    -9.8
    5049    -4.6    5073    -2.8    5094      .1    5095       1  5169.2    1.77
 5208.22     7.6 5354.46    8.19 5465.24    8.98 5556.54   11.09  5585.9   13.57
 5691.28   15.08  5741.8   11.26 5756.12    8.66 5775.48    6.93 5822.14    9.96
 5889.44   12.29 5960.74    11.8 6051.12   15.29 6477.36   19.39  6821.2   19.99
#Mann= 4 ,-1 , 0
 4619.02     .07       0  4806.2     .03       0 5208.22     .07       0
 5354.46     .15       0
Bank Sta=4806.2,5208.22
XS Rating Curve= 0 ,0
Exp/Cntr=0.3,0.1

Type RM Length L Ch R = 1 ,1481.128,157.09,1481.13,1053.17
XS GIS Cut Line= 4
     3201825.909    13836606.979     3201922.978    13836438.103
     3202173.965    13835980.163     3202834.955    13834688.618
#Sta/Elev= 30
 4525.24    3.68 4548.75    5.74 4641.91    7.25 4765.87    6.75    4793    3.29
    4798       0    4808    -5.1    4838   -10.2    4913     -13    5053    -1.7
    5163       0    5184    2.58  5198.5    5.26 5200.69    6.18 5212.97   11.41
  5234.9   15.86 5273.81   18.43 5327.36    17.9 5673.98   18.06 5712.89   16.56
 5731.31   14.99 5804.04   14.64 5834.53   15.76 5947.74   16.65    6137   15.82
 6158.22   14.93 6212.33    14.6 6411.07   15.46 6624.52   14.51  6693.1   14.85
#Mann= 4 ,-1 , 0
 4525.24     .07       0 4765.87     .03       0 5200.69     .07       0
 5834.53     .15       0
Bank Sta=4765.87,5200.69
XS Rating Curve= 0 ,0
Exp/Cntr=0.3,0.1

Chan Stop Cuts=-1
Use User Specified Reach Order=0
Composite Channel Slope=5